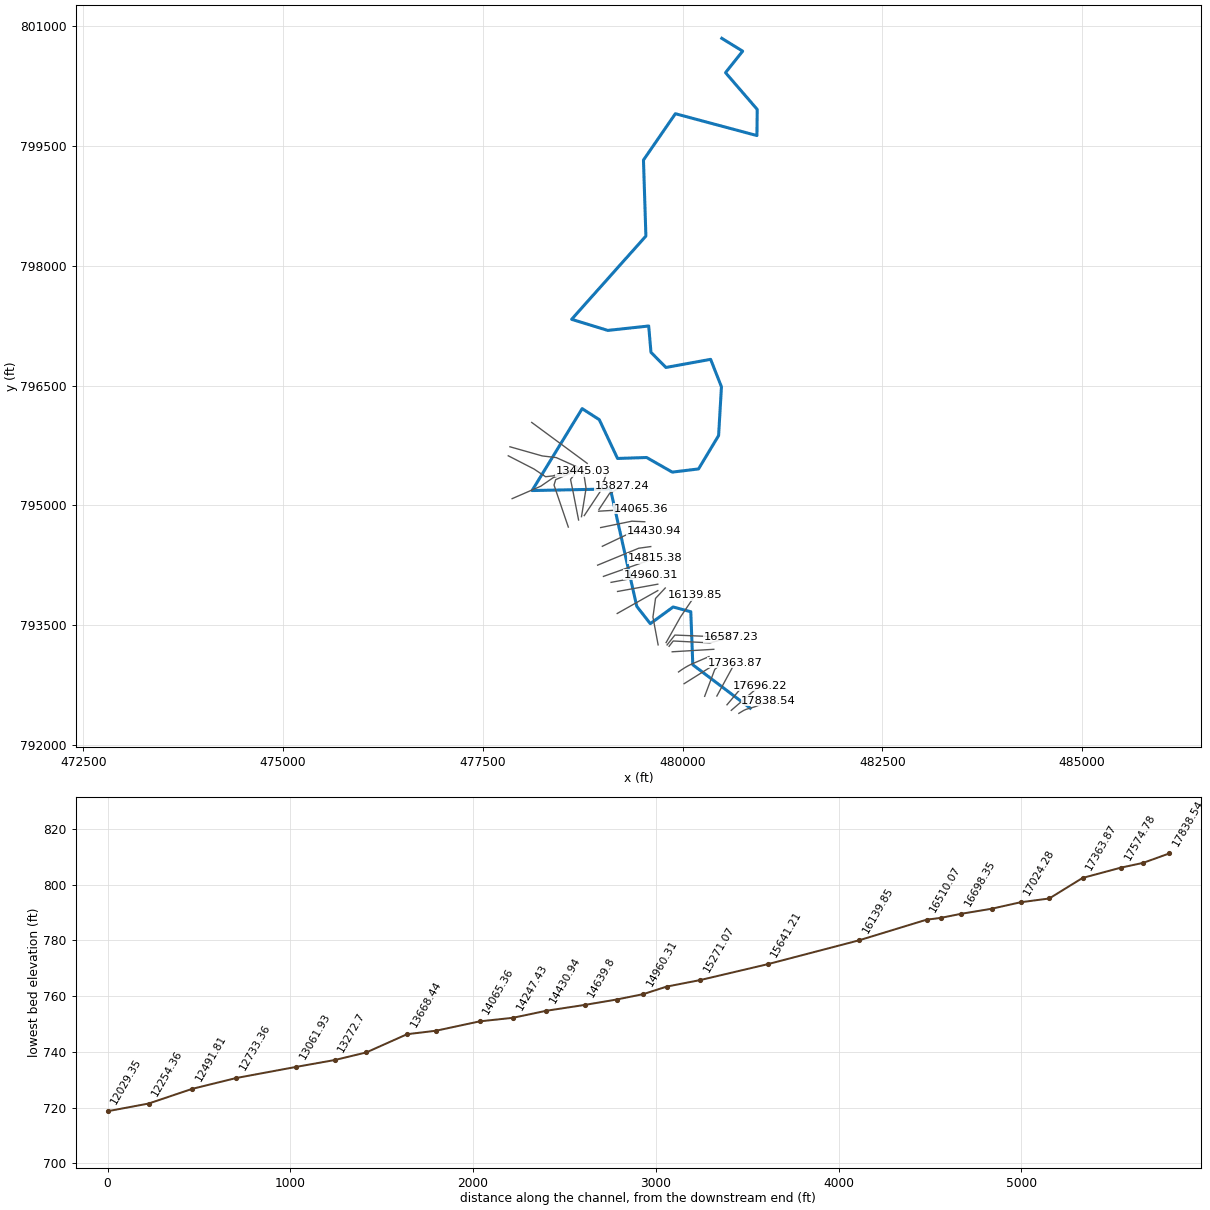
--- 5598_ras.prj (project) ---

Proj Title=5598
Current Plan=p01
Default Exp/Contr=0.3,0.1
English Units
Geom File=g01
Flow File=f01
Plan File=p01
Y Axis Title=Elevation
X Axis Title(PF)=Main Channel Distance
X Axis Title(XS)=Station
BEGIN DESCRIPTION:
RFD model 5598 exported to HEC-RAS
END DESCRIPTION:

--- 5598_ras.p01 (plan) ---

Plan Title=Plan 01
Program Version=4.10
Short Identifier=Plan 01
Geom File=g01
Flow File=f01
Subcritical Flow
Calc Critical at every XS
Secant Critical Depth

--- 5598_ras.f01 (steady flow) ---

Flow Title=Flow 01
Program Version=5.01
Number of Profiles= 6
Profile Names=10yr,25yr,50yr,100yr,100plus,500yr
River Rch & RM=5598,60,17838.54
 4921.02 7836.6310577.8513011.9118997.3920214.89
River Rch & RM=5598,60,17696.22
 4922.32 7838.7110580.6713015.3919002.4720219.55
River Rch & RM=5598,60,17574.78
 4926.45 7845.3110589.61 13026.419018.5520234.29
River Rch & RM=5598,60,17363.87
 4983.93 7937.5110714.7413180.8619244.0620441.73
River Rch & RM=5598,60,17181.67
 4988.48 7944.7810724.59   1319319261.7920457.95
River Rch & RM=5598,60,17024.28
 4992.16 7950.6710732.5713202.8319276.1420471.07
River Rch & RM=5598,60,16866.28
 4994.77 7954.8310738.2113209.7819286.2820480.34
River Rch & RM=5598,60,16698.35
 4996.07 7956.9210741.0313213.2519291.3520484.97
River Rch & RM=5598,60,16587.23
 5015.46 7988.0610783.33 13265.519367.6320555.16
River Rch & RM=5598,60,16510.07
 5017.63 7991.5210788.0213271.2819376.0620562.87
River Rch & RM=5598,60,16139.85
 5023.76 8001.3810801.4313287.8719400.2920585.21
River Rch & RM=5598,60,15641.21
 6049.88 9604.4112940.0415885.48 23192.823879.08
River Rch & RM=5598,60,15271.07
 6136.58 9741.5513124.5416111.3123522.5124167.63
River Rch & RM=5598,60,15088.51
 6154.06  9769.713162.8416158.6923591.6924229.81
River Rch & RM=5598,60,14960.31
 6156.74    977413168.69 16165.923602.22 24239.2
River Rch & RM=5598,60,14815.38
 6159.43 9778.3113174.5316173.1123612.74 24248.6
River Rch & RM=5598,60, 14639.8
  6164.8 9786.9213186.2216187.5323633.7924267.37
River Rch & RM=5598,60,14430.94
 6167.91  9791.913192.9716195.8523645.9524278.21
River Rch & RM=5598,60,14247.43
 6180.85 9812.6713221.18 16230.723696.8224323.68
River Rch & RM=5598,60,14065.36
 6183.51 9816.95   1322716237.88 23707.324333.05
River Rch & RM=5598,60,13827.24
 6186.18 9821.2313232.8116245.0623717.7924342.43
River Rch & RM=5598,60,13668.44
 6186.99 9822.54 13234.616247.2723721.0224345.32
River Rch & RM=5598,60,13445.03
 6188.63 9825.1813238.1816251.6923727.4724351.09
River Rch & RM=5598,60, 13272.7
 6190.68 9828.4713242.6516257.2223735.54 24358.3
River Rch & RM=5598,60,13061.93
 6194.39 9834.4213250.7316267.1823750.0924371.28
River Rch & RM=5598,60,12733.36
 6280.66 9971.3313435.3316493.5824080.6324661.14
River Rch & RM=5598,60,12491.81
 6281.29 9972.3413436.6916495.2624083.0724663.29
River Rch & RM=5598,60,12254.36
 6283.61 9976.0313441.6816501.3924092.0324671.18
River Rch & RM=5598,60,12029.35
 6291.57 9988.7413458.8716522.54 24122.924698.44
River Rch & RM=5598,60,11826.24
 6292.83 9990.7513461.5916525.8824127.7824702.74
River Rch & RM=5598,60,11412.36
 6317.0610029.5113514.1316590.6424222.3424786.59
River Rch & RM=5598,60,11041.94
 6323.1610039.3213527.4716607.1324246.4124808.07
River Rch & RM=5598,60,10789.18
 6326.2210044.2413534.1516615.3824258.4524818.81
River Rch & RM=5598,60,10574.26
 6329.0710048.8213540.3816623.0724269.6924828.83
River Rch & RM=5598,60,10303.52
 6333.5610056.0313550.1816635.1724287.3524844.57
River Rch & RM=5598,60,9979.407
 6338.0410063.2413559.9716647.2724305.0124860.31
River Rch & RM=5598,60,9791.108
 6342.8910071.0413570.5916660.4124324.1924877.48
River Rch & RM=5598,60, 9540.18
 6347.2910078.1413580.2816672.4124341.7124893.21
River Rch & RM=5598,60,9328.712
 6349.4810081.6813585.1116678.3924350.4624901.07
River Rch & RM=5598,60,9229.339
 6517.4310354.0113957.3617140.6825025.3925509.39
River Rch & RM=5598,60,8982.059
  6520.410358.8113963.91 17148.825037.2425520.01
River Rch & RM=5598,60,8775.094
 6527.7310370.6613980.0817168.8425066.51 25546.2
River Rch & RM=5598,60,8509.521
 6553.9810413.2914038.4317241.3825172.4125641.67
River Rch & RM=5598,60,8201.993
 6565.5210432.0114064.0217273.1525218.8125683.36
River Rch & RM=5598,60,7835.653
 6573.7410445.3414082.2317295.7725251.8225713.01
River Rch & RM=5598,60,7599.098
 6575.3110447.8814085.7117300.0825258.1225718.66
River Rch & RM=5598,60,7264.429
 6586.7210466.2714110.7417331.0425303.3325758.88
River Rch & RM=5598,60,7058.409
  6590.510472.3714119.0517341.3425318.3625772.28
River Rch & RM=5598,60,6654.721
 6600.2610488.11 14140.5 17367.925357.1325806.83
River Rch & RM=5598,60, 6415.64
 6605.4710496.4914151.9117382.0125377.7325825.16
River Rch & RM=5598,60, 6192.17
 6610.6710504.8714163.3117396.1225398.3425843.48
River Rch & RM=5598,60,5827.986
 6616.9310514.9314176.9817413.0125422.9925865.31
River Rch & RM=5598,60,5422.844
 6620.33 10520.414184.4417422.2425436.4625877.28
River Rch & RM=5598,60,4998.167
 6620.5310520.7314184.8817422.7825437.2525877.99
Boundary for River Rch & Prof#=5598,60,1
Up Type= 0
Dn Type= 2
Boundary for River Rch & Prof#=5598,60,2
Up Type= 0
Dn Type= 2
Boundary for River Rch & Prof#=5598,60,2
Up Type= 0
Dn Type= 2
Boundary for River Rch & Prof#=5598,60,2
Up Type= 0
Dn Type= 2
Boundary for River Rch & Prof#=5598,60,2
Up Type= 0
Dn Type= 2
Boundary for River Rch & Prof#=5598,60,2
Up Type= 0
Dn Type= 2

--- 5598_ras.g01 (geometry) ---

Geom Title=5598
Program Version=4.10

River Reach=5598,60
Reach XY= 30
480845.871066317792463.397465095480126.838804051 793005.93306151
480101.691517249793669.943212152479880.790504172793729.567437783
479594.963753656793520.966724768479425.450198948793737.703689203
479095.589046091795206.453757346478115.751155406795186.794310883
478742.290213168796211.662154064 478956.70018132796073.641357958
479184.998623282795588.398071438479548.954113573795600.389203221
479869.894515902795417.391254246480198.887665927795457.321824446
 480449.75514476795874.858791351480485.345738217796485.099407628
480349.929301158796828.849438056479790.901261434796727.287060559
479603.401353374796916.523359731479574.894062042797246.078903258
479063.470999569797190.828725621  478610.3460242797329.717766136
479539.824423283798371.643443227479509.442327216799323.032087013
479908.747758046799902.893440366480929.581352696799629.455960065
480933.053496957 799956.71275866480536.352005467800416.782284245
480750.761833683 800685.87927781480489.628987208800846.267371103

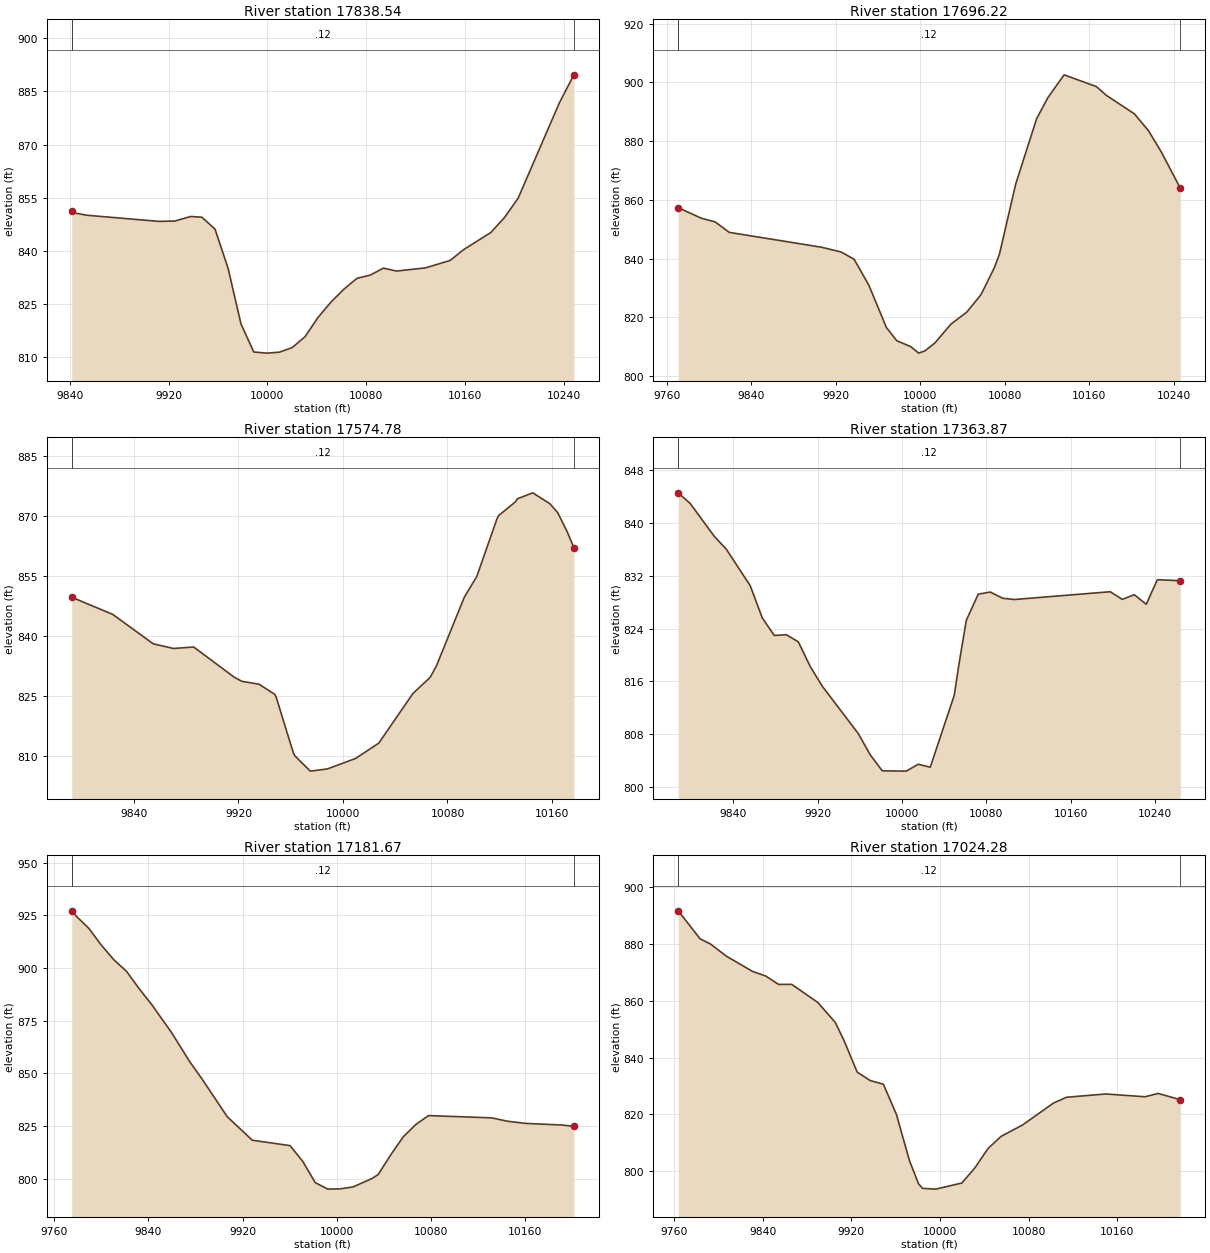
Type RM Length L Ch R = 1 ,17838.54,142.328400,142.328400,142.328400
XS GIS Cut Line= 6
480702.972045888792398.064379631480763.116136626792434.627540476
480797.726163975792449.870617676480898.240248127792478.849832511
480962.440657468792503.027006985481075.559984268792555.786378359
#Sta/Elev= 30
9841.703 851.2949844.152850.69069854.074850.05669912.152848.33799925.138848.4318
9937.886849.71299946.991849.51479957.634846.16189968.171835.16649978.664819.4073
9989.023811.50849999.383811.184310009.76 811.45310020.13812.7551 10030.5815.8266
10040.87821.184710051.25825.491110061.83829.183110072.52832.2693 10083.2833.1802
10093.89835.145610104.57834.326510128.02835.226810147.95837.325910158.91840.3796
10180.85 845.19510191.81849.382610202.92854.850610236.29881.724410248.04889.6592
#Mann= 3 , 0 , 0
9841.703    0.12       09841.703    0.12       010248.04    0.12       0
#XS Ineff= 2 , 0
       0                               0
Bank Sta=9841.703,10248.04
Exp/Cntr=0.3,0.1

Type RM Length L Ch R = 1 ,17696.22,121.431300,121.431300,121.431300
XS GIS Cut Line= 2
480608.536635846792436.159679323480967.911635846792746.923568189
#Sta/Elev= 30
9771.028 857.3129792.794853.73469806.014852.46779819.234848.9149 9906.85843.8361
9924.997842.24679937.427839.77279951.437830.90839968.003816.53429977.878812.0073
9991.098 810.014 9998.58807.805510004.32808.531910013.87811.255810029.16817.7043
10043.98821.7319 10057.2 827.56710059.73829.284710070.42837.080310075.02841.5487
10090.31 865.26410110.08887.525810120.89894.807510136.17902.534110166.75 898.527
10176.18895.540410202.62889.270310215.84883.6036 10227.9876.457710246.13863.9353
#Mann= 3 , 0 , 0
9771.028    0.12       09771.028    0.12       010246.13    0.12       0
#XS Ineff= 2 , 0
       0                               0
Bank Sta=9771.028,10246.13
Exp/Cntr=0.3,0.1

Type RM Length L Ch R = 1 ,17574.78,210.916100,210.916100,210.916100
XS GIS Cut Line= 2
480554.717191368792505.604123756480802.981080234792799.006901547
#Sta/Elev= 30
 9792.38849.67489823.781845.37539854.743838.00579870.224836.83939885.706837.2062
9916.668829.65959922.584 828.6039935.684827.87939947.631825.37899948.783824.7221
9961.883810.80249963.112809.94519974.982806.09419988.082806.643910009.56809.2563
10027.38813.102510053.58825.568610066.68829.573710071.48832.430910092.88849.6884
10102.44854.911210117.92869.368410119.08870.123610132.18873.647210133.41874.3459
10145.28875.851510158.38873.123310164.37870.886410171.48866.202510176.72 862.145
#Mann= 3 , 0 , 0
 9792.38    0.12       0 9792.38    0.12       010176.72    0.12       0
#XS Ineff= 2 , 0
       0                               0
Bank Sta=9792.38,10176.72
Exp/Cntr=0.3,0.1

Type RM Length L Ch R = 1 ,17363.87,182.200200,182.200200,182.200200
XS GIS Cut Line= 2
480427.981080234792614.979123756480655.411635846793033.381901562
#Sta/Elev= 30
9787.898 844.5959799.303842.96759822.067837.99939833.449836.05929856.213830.4938
9867.594825.63739878.976822.95499890.358823.0746 9901.74822.00589913.122818.2452
9924.504815.26739958.649808.07729970.108 804.8379981.413  802.4310004.18 802.379
10015.56803.420910026.94802.9748 10049.7813.884510053.86818.284710061.09825.2395
10072.47 829.22210083.85829.542410095.74828.598410106.61828.411710197.67829.5921
10209.05828.431710220.43829.143610231.81827.690710242.32831.412610264.12 831.264
#Mann= 3 , 0 , 0
9787.898    0.12       09787.898    0.12       010264.12    0.12       0
#XS Ineff= 2 , 0
       0                               0
Bank Sta=9787.898,10264.12
Exp/Cntr=0.3,0.1

Type RM Length L Ch R = 1 ,17181.67,157.384300,157.384300,157.384300
XS GIS Cut Line= 3
480275.203302473792611.506901547480401.939413577792948.312457085
480452.286635846792991.715234861
#Sta/Elev= 30
9774.991927.17879778.723924.68359789.408918.89839800.092910.88769810.777903.9188
9821.461898.47049832.146890.26329842.831882.70149859.597869.47319874.884855.7726
9885.569 847.3579906.938829.44669928.307818.2308 9960.36815.67599971.045808.2734
 9981.73798.09119992.414 795.011 10003.1795.160710013.78796.041310029.96800.0576
10035.15801.931110045.84811.284610056.52819.893110067.21825.736910077.89 829.933
10131.31828.866510145.09827.257410160.41826.2256 10191.7825.439310201.33 824.805
#Mann= 3 , 0 , 0
9774.991    0.12       09774.991    0.12       010201.33    0.12       0
#XS Ineff= 2 , 0
       0                               0
Bank Sta=9774.991,10201.33
Exp/Cntr=0.3,0.1

Type RM Length L Ch R = 1 ,17024.28,158.000900,158.000900,158.000900
XS GIS Cut Line= 2
480018.258858025792769.493012652480401.939413577793010.812457085
#Sta/Elev= 30
9763.648891.70789783.425881.83519792.774 880.0169807.052 875.7479830.679870.3649
9842.492868.76599854.306 865.7759866.119865.79979889.746859.3949 9905.47852.3603
9913.374845.95769925.187834.88599937.001831.89239948.814830.63419960.628819.9699
9972.441803.6379  9980.6795.51559984.255793.92389996.068793.6494 10019.7795.8028
10031.51801.165910043.32807.944610055.14812.249910074.51816.261410102.39823.9715
 10114.2826.020110149.64827.175210185.08826.1949 10196.9827.366810216.91825.1487
#Mann= 3 , 0 , 0
9763.648    0.12       09763.648    0.12       010216.91    0.12       0
#XS Ineff= 2 , 0
       0                               0
Bank Sta=9763.648,10216.91
Exp/Cntr=0.3,0.1

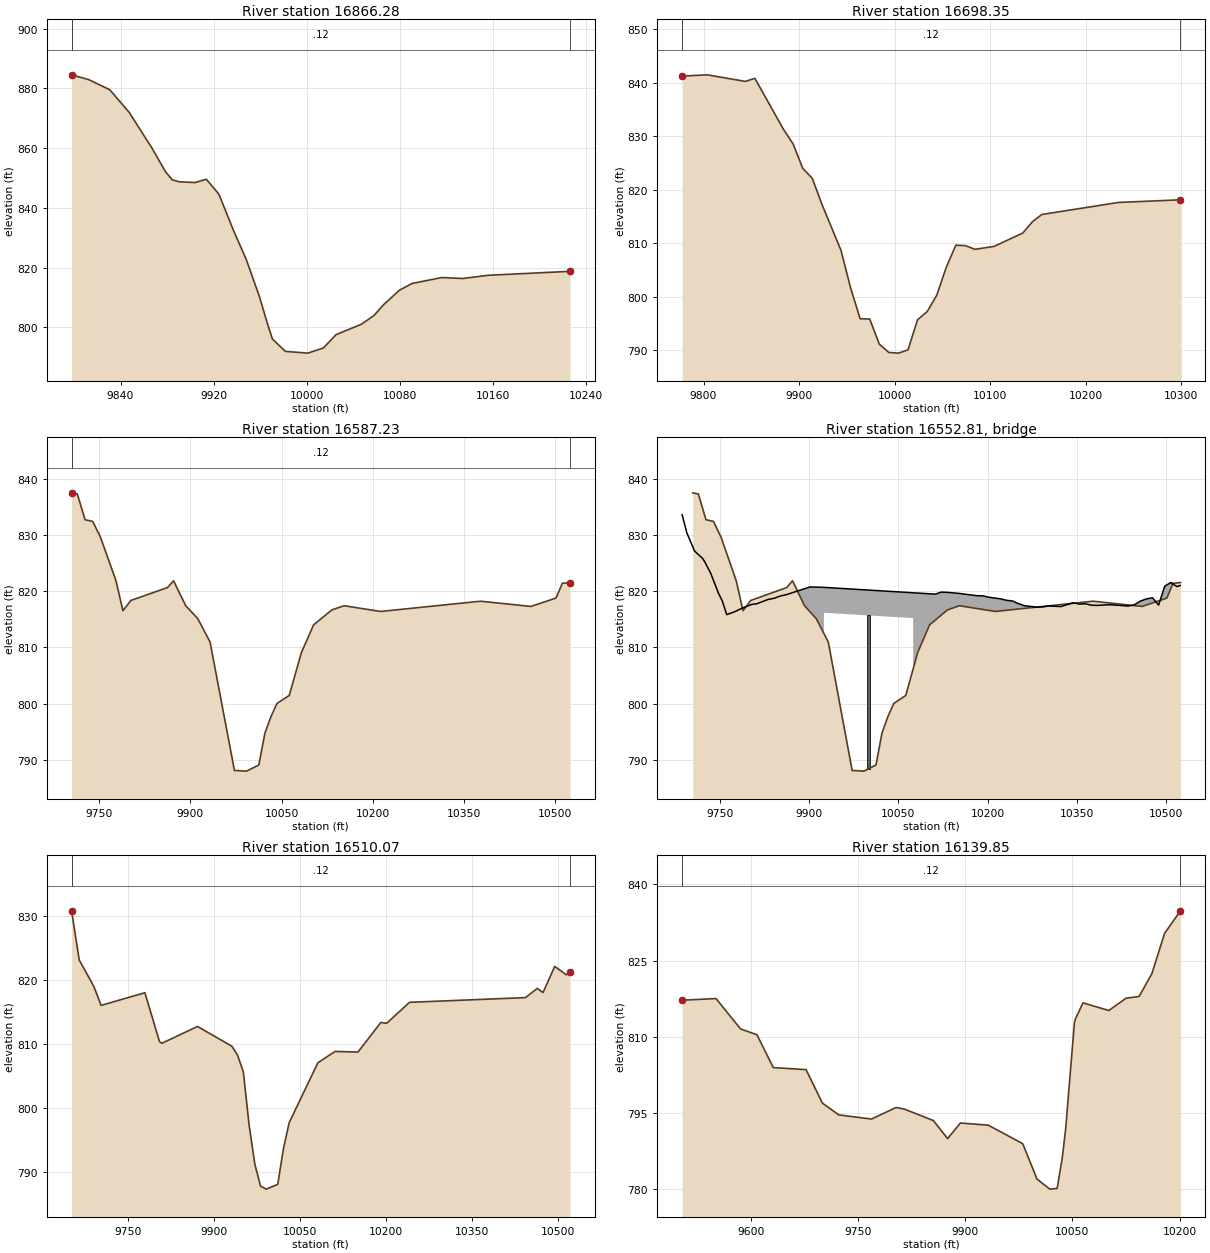
Type RM Length L Ch R = 1 ,16866.28,167.936000,167.936000,167.936000
XS GIS Cut Line= 6
479948.271656722792916.351572186479986.801292807792943.817294821
480025.866091609792968.882395923480064.656579047792991.293962285
480101.805501223793010.417682022480329.601534426793108.647290513
#Sta/Elev= 30
9797.919884.56639812.818882.93559830.743 879.5669847.426871.99659866.858860.1175
 9878.74852.05459884.461849.38569890.621848.72799903.879848.47879913.748  849.58
9923.868844.92239925.297843.87939936.836832.65639948.083822.6871 9959.33810.3441
9966.395801.05019970.577796.04999981.705791.9139   10001791.325510014.32793.0459
10025.21 797.501   10047800.997710057.89803.936910065.84807.449710079.68812.3862
10090.57814.662710116.26816.658510134.15816.329310155.93817.402510226.31818.7258
#Mann= 3 , 0 , 0
9797.919    0.12       09797.919    0.12       010226.31    0.12       0
#XS Ineff= 2 , 0
       0                               0
Bank Sta=9797.919,10226.31
Exp/Cntr=0.3,0.1

Type RM Length L Ch R = 1 ,16698.35,111.118400,111.118400,111.118400
XS GIS Cut Line= 2
479868.953302473793168.798568189480389.786635846793200.048568189
#Sta/Elev= 30
9777.583 841.2499803.676841.48859843.748840.26299853.766840.8318 9883.82831.2624
9893.838828.56549903.856824.00639913.874 822.1539923.892817.33319943.928808.6831
9953.946801.68569963.964795.91689973.982795.8719    9984 791.1829994.018789.6119
10004.04789.496410014.05790.101110024.07795.729610034.09797.244110044.11  800.29
10054.13805.526410064.14809.664910074.16809.576210084.18808.889310104.22 809.437
10134.27811.935310144.29814.039710154.31815.404310234.45817.645810299.35818.1411
#Mann= 3 , 0 , 0
9777.583    0.12       09777.583    0.12       010299.35    0.12       0
#XS Ineff= 2 , 0
       0                               0
Bank Sta=9777.583,10299.35
Exp/Cntr=0.3,0.1

Type RM Length L Ch R = 1 ,16587.23,77.153900,77.153900,77.153900
XS GIS Cut Line= 4
479829.797684759793237.591017067479881.881018072793303.997267053
480340.214351416793280.559767053480607.141434759793350.872267053
#Sta/Elev= 30
9704.727837.46139714.143837.25439726.852832.69179739.561832.37729752.269829.5717
9777.687821.86529789.122816.52549802.258818.34889862.336820.63069872.349821.8381
9892.375817.41899912.401815.08529932.428810.9568 9972.48788.15749992.506 788.035
10012.53789.127210022.55794.768210032.56797.734410042.57800.0715 10062.6801.4781
10082.62809.108110102.65 814.01310132.69816.670310152.71817.409410212.79816.3913
 10377.1 818.21210459.82817.285710501.19818.768710511.53821.390310524.09821.5297
#Mann= 3 , 0 , 0
9704.727    0.12       09704.727    0.12       010524.09    0.12       0
#XS Ineff= 2 , 0
       0                               0
Bank Sta=9704.727,10524.09
Exp/Cntr=0.3,0.1

Type RM Length L Ch R = 3 ,16552.81,,,
BEGIN DESCRIPTION:
END DESCRIPTION:
Bridge Culvert--1,0,-1,-1, 0
Deck Dist Width WeirC Skew NumUp NumDn MinLoCord MaxHiCord MaxSubmerge Is_Ogee
20.696400,35.761100,2.6,0, 55, 55, , , 0.95, 0, 0,0,,
 9686.84 9694.68 9707.75 9721.24 9724.46 9734.74 9748.23 9754.25 9761.73 9775.22
 9788.72 9802.21 9806.80 9811.52 9831.55 9841.56 9851.58 9861.59 9901.66 9925.03
 9925.0310074.9710074.9710112.3310122.0010132.0110152.0310182.0310192.0310202.03
10222.0310232.0310242.0310252.0310262.0310282.2110292.4710302.7210323.2410343.75
10354.0010364.2610374.5210384.7710405.2810436.0510446.3110456.5710466.8210477.08
10487.3310497.5910507.8510518.1010523.60
  833.57  830.37  827.12  825.81  825.28  823.20  819.54  818.28  815.83  816.34
  817.04  817.58  817.71  817.73  818.53  818.73  819.13  819.36  820.75  820.67
  820.67  819.71  819.71  819.47  819.83  819.79  819.60  819.19  819.16  818.92
  818.63  818.37  818.25  817.77  817.42  817.16  817.20  817.37  817.26  817.94
  817.70  817.76  817.50  817.47  817.59  817.36  817.56  818.22  818.62  818.83
  817.52  820.88  821.54  820.80  821.00
 -166.43 -169.63 -172.88 -174.19 -174.72 -176.80 -180.46 -181.72 -184.17 -183.66
 -182.96 -182.42 -182.29 -182.27 -181.47 -181.27 -180.87 -180.64 -179.25 -179.33
  816.17  815.21 -180.29 -180.53 -180.17 -180.21 -180.40 -180.81 -180.84 -181.08
 -181.37 -181.63 -181.75 -182.23 -182.58 -182.84 -182.80 -182.63 -182.74 -182.06
 -182.30 -182.24 -182.50 -182.53 -182.41 -182.64 -182.44 -181.78 -181.38 -181.17
 -182.48 -179.12 -178.46 -179.20 -179.00
 9686.84 9694.68 9707.75 9721.24 9724.46 9734.74 9748.23 9754.25 9761.73 9775.22
 9788.72 9802.21 9806.80 9811.52 9831.55 9841.56 9851.58 9861.59 9901.66 9925.03
 9925.0310074.9710074.9710112.3310122.0010132.0110152.0310182.0310192.0310202.03
10222.0310232.0310242.0310252.0310262.0310282.2110292.4710302.7210323.2410343.75
10354.0010364.2610374.5210384.7710405.2810436.0510446.3110456.5710466.8210477.08
10487.3310497.5910507.8510518.1010523.60
  833.57  830.37  827.12  825.81  825.28  823.20  819.54  818.28  815.83  816.34
  817.04  817.58  817.71  817.73  818.53  818.73  819.13  819.36  820.75  820.67
  820.67  819.71  819.71  819.47  819.83  819.79  819.60  819.19  819.16  818.92
  818.63  818.37  818.25  817.77  817.42  817.16  817.20  817.37  817.26  817.94
  817.70  817.76  817.50  817.47  817.59  817.36  817.56  818.22  818.62  818.83
  817.52  820.88  821.54  820.80  821.00
 -166.43 -169.63 -172.88 -174.19 -174.72 -176.80 -180.46 -181.72 -184.17 -183.66
 -182.96 -182.42 -182.29 -182.27 -181.47 -181.27 -180.87 -180.64 -179.25 -179.33
  816.17  815.21 -180.29 -180.53 -180.17 -180.21 -180.40 -180.81 -180.84 -181.08
 -181.37 -181.63 -181.75 -182.23 -182.58 -182.84 -182.80 -182.63 -182.74 -182.06
 -182.30 -182.24 -182.50 -182.53 -182.41 -182.64 -182.44 -181.78 -181.38 -181.17
 -182.48 -179.12 -178.46 -179.20 -179.00
Pier Skew, UpSta & Num, DnSta & Num=  ,10000.00, 2 ,10000.00, 2 , 0 , 0 , 0 ,,
    4.00    4.00
 -179.81  820.19
    4.00    4.00
 -179.81  820.19
BR Coef=-1 , 0 , 0 ,, 0 ,,,0.8,0,1,0,
WSPro=,,,, 1 ,,,, 0 ,,,, 0 ,,,,-1 ,-1 ,-1 , 0 , 0 , 0 , 0 , 0
BC Design=,, 0 ,, 0 ,,,,,,

Type RM Length L Ch R = 1 ,16510.07,370.226300,370.226300,370.226300
XS GIS Cut Line= 4
479805.058101416793254.518100396479902.714351416793378.216017067
480410.526851416793357.382683709480611.047684789793397.747267053
#Sta/Elev= 30
9650.875830.8101 9664.23823.14399689.711819.02299702.452816.05829778.897818.0354
9804.378810.41639808.476 810.1419870.814812.77259930.864 809.6849940.872 808.278
9950.881805.64439960.889797.42379970.898791.29899980.906787.86049990.915787.3953
10010.93788.140610020.94793.738910030.95797.771510080.99 807.10710111.02808.8729
10151.05808.779710191.08813.402910201.09813.261510241.12816.536110443.69817.2736
10464.09818.708910474.29818.069310494.69822.142410515.09820.828210521.26821.2745
#Mann= 3 , 0 , 0
9650.875    0.12       09650.875    0.12       010521.26    0.12       0
#XS Ineff= 2 , 0
       0                               0
Bank Sta=9650.875,10521.26
Exp/Cntr=0.3,0.1

Type RM Length L Ch R = 1 ,16139.85,498.641100,498.641100,498.641100
XS GIS Cut Line= 3
479792.853765428793283.598915413479972.975293219 793604.77947098
480157.437098771 793878.21697098
#Sta/Elev= 30
9503.263817.1851 9550.73817.50949585.125811.52289608.056810.38439630.986803.9143
9676.847803.50919699.777796.91549722.708794.59239768.569793.77919802.964796.0516
9814.429795.74289855.198793.47949875.123 789.9229893.004792.99539932.082792.5723
9980.333788.928510000.29781.969210018.17779.975210028.58780.107810036.05786.4588
10040.65792.100810052.71812.678610053.93813.425810064.77816.661510100.96815.1603
10125.09817.573810143.34817.917410161.27822.4241 10179.1830.361110201.34834.7882
#Mann= 3 , 0 , 0
9503.263    0.12       09503.263    0.12       010201.34    0.12       0
#XS Ineff= 2 , 0
       0                               0
Bank Sta=9503.263,10201.34
Exp/Cntr=0.3,0.1

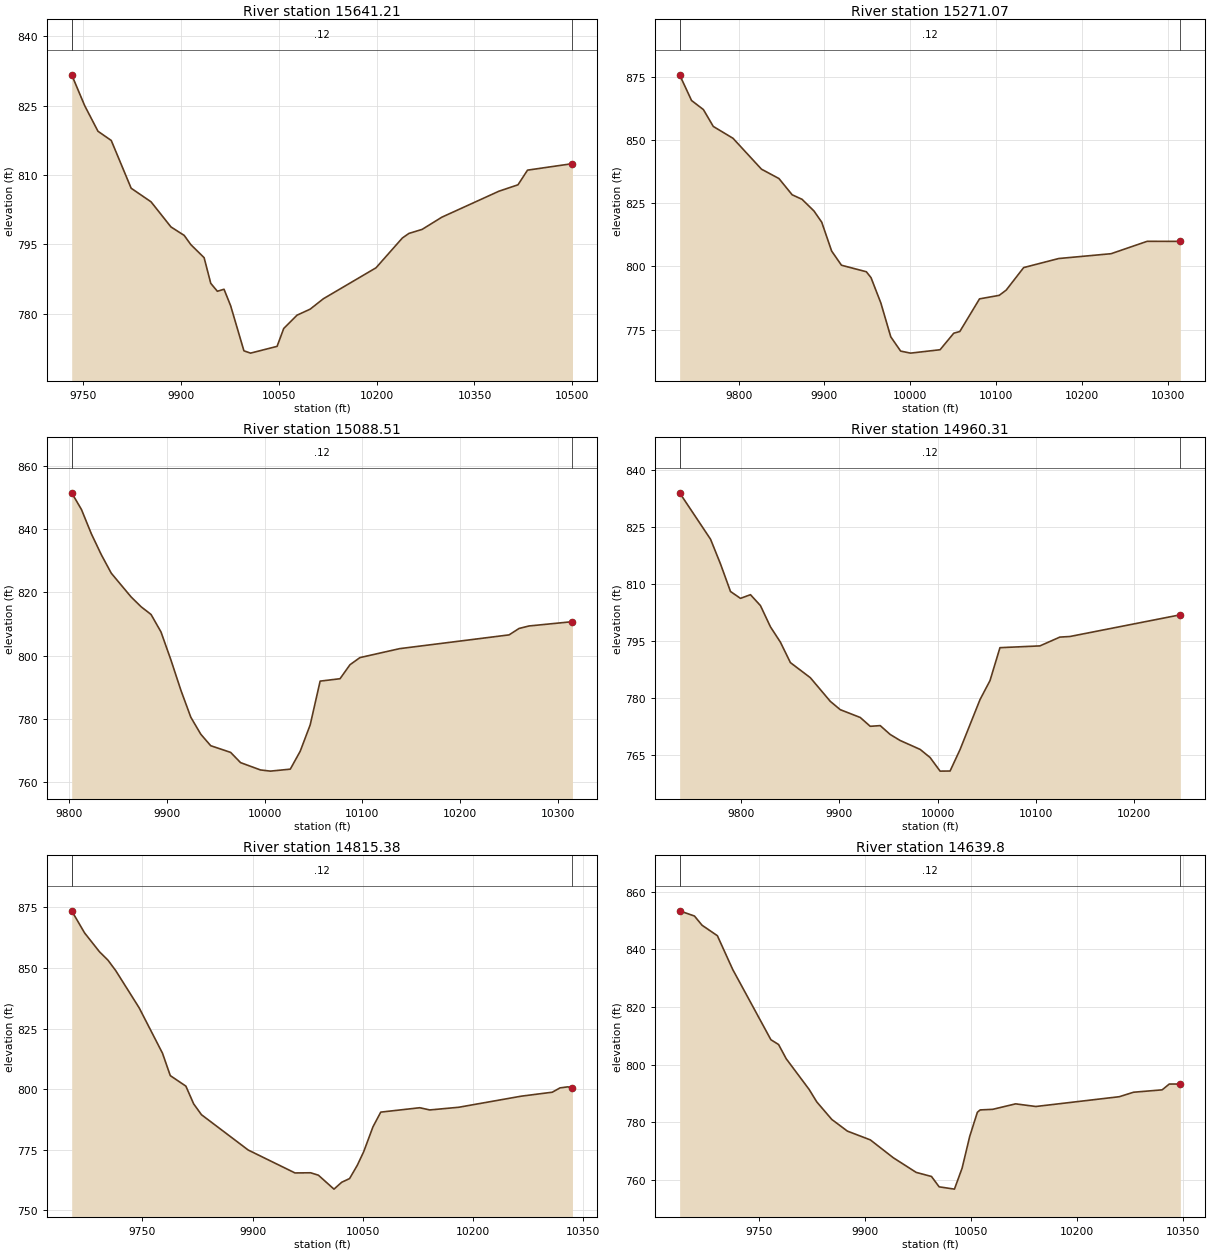
Type RM Length L Ch R = 1 ,15641.21,370.136600,370.136600,370.136600
XS GIS Cut Line= 4
479693.027376533793255.387109861479627.923209906  793602.6093321
479660.475293219  793836.9843321 479782.00307098793967.192665413
#Sta/Elev= 30
9732.258831.65569752.213824.96929772.561819.4422 9792.91817.45259823.433807.1167
9853.955804.17339884.478798.74249904.827796.90179915.001794.9067 9935.35792.0846
9945.524786.54019955.698784.81559965.872785.25649976.047 781.6769996.395771.9316
10006.57771.431410047.27772.897510057.44 776.76710077.79779.639510098.04780.9497
10118.23783.1972   10199789.896810239.38796.341610249.48797.336910269.67798.2046
10299.96800.849210387.41806.464810416.72807.855210431.38811.030110500.27 812.434
#Mann= 3 , 0 , 0
9732.258    0.12       09732.258    0.12       010500.27    0.12       0
#XS Ineff= 2 , 0
       0                               0
Bank Sta=9732.258,10500.27
Exp/Cntr=0.3,0.1

Type RM Length L Ch R = 1 ,15271.07,182.557600,182.557600,182.557600
XS GIS Cut Line= 2
479180.874598801793648.182248756479688.687098771793934.640582085
#Sta/Elev= 30
9731.381875.69719745.257 865.552 9759.08861.95629770.562855.29969793.524 850.617
9826.671838.41769847.024 834.7119862.412828.29099873.894826.5081 9887.73821.9232
9896.856817.44939908.338 806.0859919.819800.4529 9948.79797.87349954.263795.5225
9965.744785.46249977.226772.15599988.707766.527310000.19765.719610034.63767.0587
10050.56773.5968 10057.6774.259410080.56787.162610103.52788.555610111.62790.6273
10131.97799.529210172.68803.097810233.74805.008410275.74809.902910314.42809.8825
#Mann= 3 , 0 , 0
9731.381    0.12       09731.381    0.12       010314.42    0.12       0
#XS Ineff= 2 , 0
       0                               0
Bank Sta=9731.381,10314.42
Exp/Cntr=0.3,0.1

Type RM Length L Ch R = 1 ,15088.51,128.205400,128.205400,128.205400
XS GIS Cut Line= 2
479185.214876533793923.789887637479688.687098771794014.935720965
#Sta/Elev= 30
 9802.96851.55449812.904 846.2879823.066838.55529833.229831.94839843.392826.0958
9863.717818.55289873.879815.46399884.042813.01859894.204807.48049904.367798.5954
9914.529789.01159924.692780.45119934.854775.08399945.017771.44469965.342769.3281
9975.505766.0853 9995.83763.767410005.99 763.39210026.32764.016310036.48769.7113
10046.64778.0443 10056.8791.901310077.13792.666210087.29797.092210097.46799.3559
10138.11802.196810249.89806.551110260.06808.587610270.22809.374410314.62810.7401
#Mann= 3 , 0 , 0
 9802.96    0.12       0 9802.96    0.12       010314.62    0.12       0
#XS Ineff= 2 , 0
       0                               0
Bank Sta=9802.96,10314.62
Exp/Cntr=0.3,0.1

Type RM Length L Ch R = 1 ,14960.31,144.925800,144.925800,144.925800
XS GIS Cut Line= 2
479104.022746921794037.722179323479605.758858025794131.472179323
#Sta/Elev= 30
9737.101833.93459768.615821.71889778.788815.20229788.961807.96399799.134806.1573
9809.307807.1218 9819.48804.25579829.653 798.6729839.826794.63179849.999789.2521
9870.345785.27429890.692779.05029900.865776.85739921.211774.80849931.384772.4846
9941.557772.6648 9951.73770.33719961.903 768.7499982.249 766.4059992.422764.2664
 10002.6760.686810012.77760.715910022.94766.358110043.29779.517710053.46784.5076
10063.63793.181610104.33793.644810124.67795.963410134.85 796.11610247.52801.8357
#Mann= 3 , 0 , 0
9737.101    0.12       09737.101    0.12       010247.52    0.12       0
#XS Ineff= 2 , 0
       0                               0
Bank Sta=9737.101,10247.52
Exp/Cntr=0.3,0.1

Type RM Length L Ch R = 1 ,14815.38,175.584300,175.584300,175.584300
XS GIS Cut Line= 2
479008.536635846  794112.3749571 479650.89774695794339.805512637
#Sta/Elev= 30
9653.965873.6136 9671.43864.52349691.792856.70779703.255853.27099713.863848.9504
9745.688833.62339777.512814.85169788.121805.60399809.337801.26459819.946793.9371
9830.554789.47019894.203 774.8869957.853 765.436 9979.07 765.5039989.678764.5063
10010.89758.757410021.38761.590510032.11763.114310042.72768.660610051.34774.2206
10063.94784.477110074.54790.536410127.59792.348110141.23791.436910180.63792.5418
10265.49797.108410307.93798.755710318.53800.541310329.14800.9692 10335.4800.4465
#Mann= 3 , 0 , 0
9653.965    0.12       09653.965    0.12       0 10335.4    0.12       0
#XS Ineff= 2 , 0
       0                               0
Bank Sta=9653.965,10335.4
Exp/Cntr=0.3,0.1

Type RM Length L Ch R = 1 , 14639.8,208.852500,208.852500,208.852500
XS GIS Cut Line= 3
 478935.61996913  794252.9999571479449.508858025794464.805512637
479600.550524712794485.638845995
#Sta/Elev= 30
9637.652853.34099658.614851.5379 9669.43848.33099691.062844.71119712.694833.0235
9766.775808.62619777.591806.97529788.407802.03839820.855791.38129831.671787.0601
9852.839780.99299874.936776.93419907.384773.89369939.832767.7019 9972.28762.6136
9993.913761.193710004.73757.605210026.36756.809710037.18764.069310047.99775.1129
10058.81783.466710062.78784.283210080.44784.482410112.89786.3865 10141.5785.4711
10259.59788.865710279.78 790.42210320.16791.245510330.25793.257510345.95793.2655
#Mann= 3 , 0 , 0
9637.652    0.12       09637.652    0.12       010345.95    0.12       0
#XS Ineff= 2 , 0
       0                               0
Bank Sta=9637.652,10345.95
Exp/Cntr=0.3,0.1

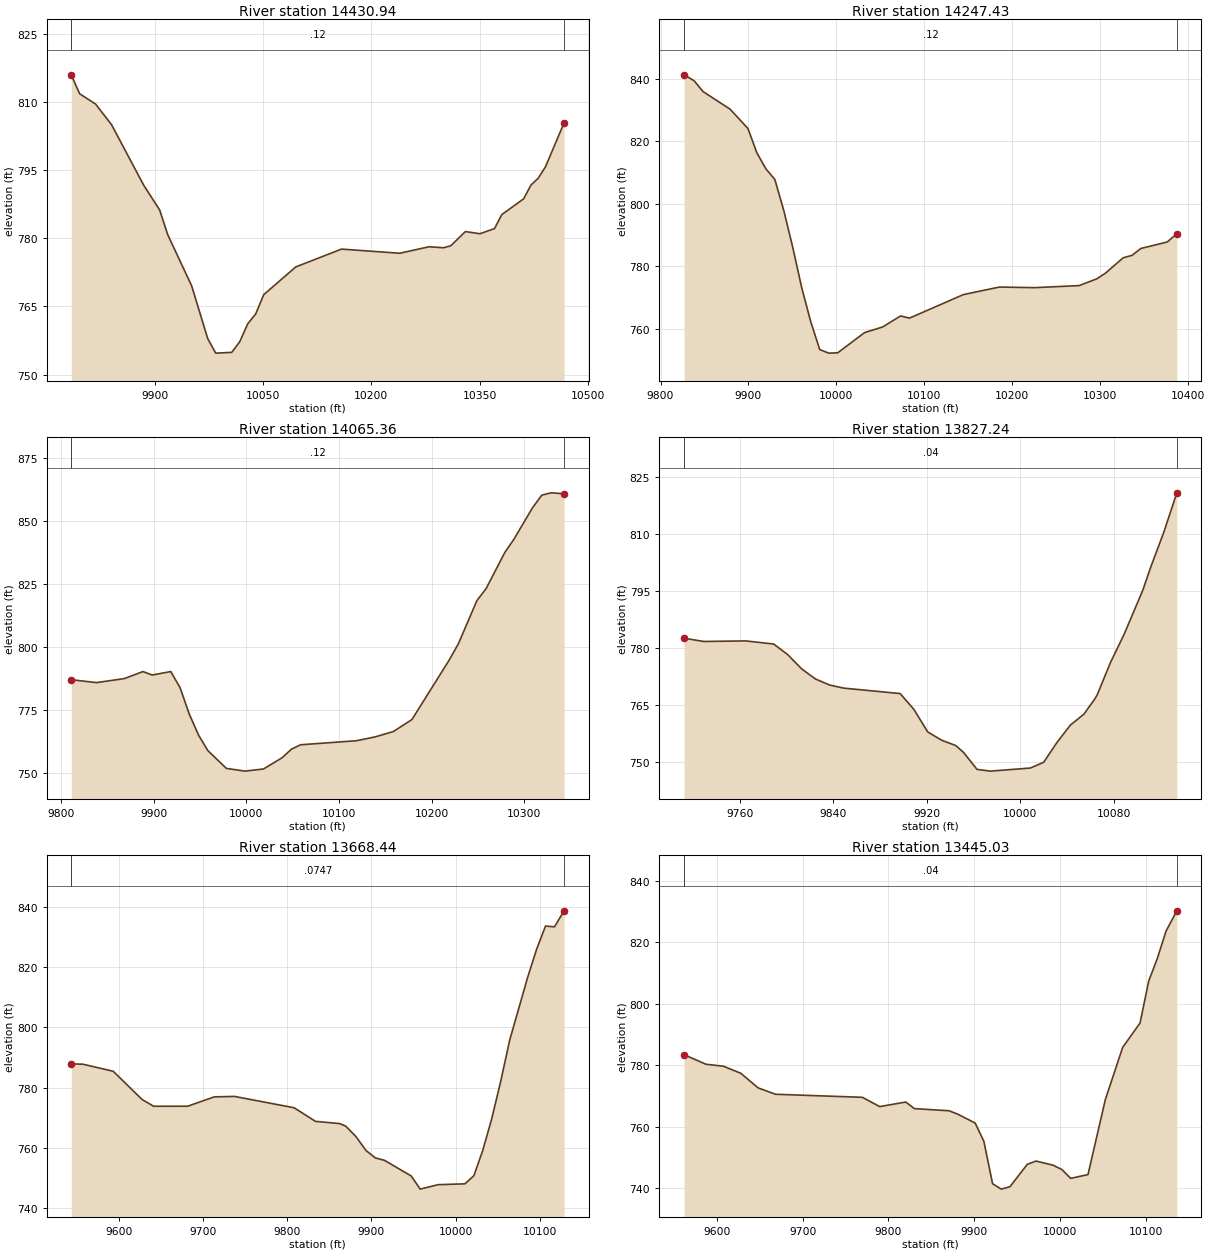
Type RM Length L Ch R = 1 ,14430.94,183.512800,183.512800,183.512800
XS GIS Cut Line= 3
478994.647746921794489.111068204479303.675524712794636.680512637
479640.481080234794680.083290428
#Sta/Elev= 30
9784.803815.97179796.275811.81279818.438809.53549840.601 804.9729884.928791.7051
9907.091786.23969918.173780.82579951.418769.52249973.581757.94339984.663754.7283
10006.83754.893110017.91757.227810028.99761.172710040.07763.362510051.15767.5904
10095.48 773.69910158.84777.6219 10239.5776.706110279.83778.1316   10300777.9186
10310.08778.354410330.25781.481710350.41780.998910370.58 782.13810380.66785.2094
10410.91 788.69210420.99791.703910431.07793.221210441.16795.737610466.85 805.408
#Mann= 3 , 0 , 0
9784.803    0.12       09784.803    0.12       010466.85    0.12       0
#XS Ineff= 2 , 0
       0                               0
Bank Sta=9784.803,10466.85
Exp/Cntr=0.3,0.1

Type RM Length L Ch R = 1 ,14247.43,182.069600,182.069600,182.069600
XS GIS Cut Line= 3
478973.814413607794723.486068204479364.439413577794803.347179309
479525.897746921794796.402734861
#Sta/Elev= 30
9826.744841.27399838.161839.39999848.368835.90789878.988830.31099899.402 824.103
9909.609816.27339919.816811.19319930.023807.7662 9940.23 797.7699950.436785.9572
9960.643773.0341 9970.85762.21699981.057753.33459991.264 752.19310001.47752.2917
10032.09758.7741 10052.5760.553310072.92764.090410083.13763.400210144.37770.9255
10185.19773.337410225.45773.153510276.06773.807810296.07775.974810306.08777.8277
 10326.1782.713410336.11783.486510346.12785.688210376.15787.760810387.06790.3977
#Mann= 3 , 0 , 0
9826.744    0.12       09826.744    0.12       010387.06    0.12       0
#XS Ineff= 2 , 0
       0                               0
Bank Sta=9826.744,10387.06
Exp/Cntr=0.3,0.1

Type RM Length L Ch R = 1 ,14065.36,238.124400,238.124400,238.124400
XS GIS Cut Line= 2
478947.772746921794928.347179309479479.022746921794959.597179309
#Sta/Elev= 30
9810.965787.09869838.239785.94479868.291787.54579888.326790.32049898.343788.9529
9918.378790.31989928.395783.98629938.412773.4532 9948.43765.13479958.447759.0292
9978.481751.99219998.516750.911210018.55751.763910038.59756.2032 10048.6759.5849
10058.62761.346710118.72762.933810138.76764.438610158.79766.580510178.83771.3347
 10218.9794.769710228.91801.261610248.95818.380410258.97823.1842   10279837.3902
10289.02842.726410309.05855.163210319.07860.150510329.09 861.07410343.13860.7187
#Mann= 3 , 0 , 0
9810.965    0.12       09810.965    0.12       010343.13    0.12       0
#XS Ineff= 2 , 0
       0                               0
Bank Sta=9810.965,10343.13
Exp/Cntr=0.3,0.1

Type RM Length L Ch R = 1 ,13827.24,158.797800,158.797800,158.797800
XS GIS Cut Line= 3
478952.981080234794950.916623771479084.925524712795150.569401532
479244.647746921795239.111068204
#Sta/Elev= 30
9712.253782.53339729.134781.67129765.093781.82119789.066780.99429801.053778.2052
9813.039774.44729824.739771.81029837.012770.20489848.999769.39729897.289767.9667
9908.931 763.8689920.917757.86529932.904755.6842 9944.89754.29779951.651752.4665
9963.085748.02669974.518747.560510008.82 748.37610020.25749.904410031.69755.1554
10043.12759.695210054.55762.519610063.83766.492110065.99767.601410077.42776.1533
10088.86783.412510105.08795.156710111.72801.120310123.16810.498810134.19 820.782
#Mann= 3 , 0 , 0
9712.253    0.04       09712.253    0.04       010134.19    0.04       0
#XS Ineff= 2 , 0
       0                               0
Bank Sta=9712.253,10134.19
Exp/Cntr=0.3,0.1

Type RM Length L Ch R = 1 ,13668.44,223.411400,223.411400,223.411400
XS GIS Cut Line= 3
478768.543107718794873.569918156478964.723663241795168.708807051
479042.848663241795385.722695932
#Sta/Elev= 30
9543.719787.90649557.444787.80619593.467785.46139627.641776.10829641.497773.8314
9681.835773.84869713.543776.95519737.558777.09869808.287773.33259833.619768.8214
9862.481768.07519869.642767.2066 9881.65763.78339893.658759.11859904.797756.6625
9915.426  755.89 9947.31750.67199957.939746.31059979.195747.789910011.08748.0666
10021.71750.780710032.34759.270410042.96769.776110053.59782.197910064.22795.8247
10085.48816.618610096.11825.953410106.73833.685910117.36833.426810128.76838.7441
#Mann= 3 , 0 , 0
9543.719  0.0747       09543.719  0.0747       010128.76  0.0747       0
#XS Ineff= 2 , 0
       0                               0
Bank Sta=9543.719,10128.76
Exp/Cntr=0.3,0.1

Type RM Length L Ch R = 1 ,13445.03,172.327400,172.327400,172.327400
XS GIS Cut Line= 3
478733.820885479794859.681029275478791.112552106795213.847695932
478758.126441002795427.389362618
#Sta/Elev= 30
9561.542783.4877 9587.19780.3733 9607.45779.7459 9627.71777.4475 9647.97772.6971
 9668.23 770.618 9769.53769.6306 9789.79766.6131 9820.18768.0864 9830.31765.9482
 9870.83765.2484 9880.96764.1302 9901.22761.2412 9911.35755.27559921.478741.5223
9931.597 739.7649941.716 740.5459961.953747.81879972.071748.90149992.309747.5301
10002.43746.108310012.55743.263410032.78744.492410053.02768.886810073.26785.8829
10093.49793.779510103.61807.428910113.73814.847510123.85823.689610136.39830.2792
#Mann= 3 , 0 , 0
9561.542    0.04       09561.542    0.04       010136.39    0.04       0
#XS Ineff= 2 , 0
       0                               0
Bank Sta=9561.542,10136.39
Exp/Cntr=0.3,0.1

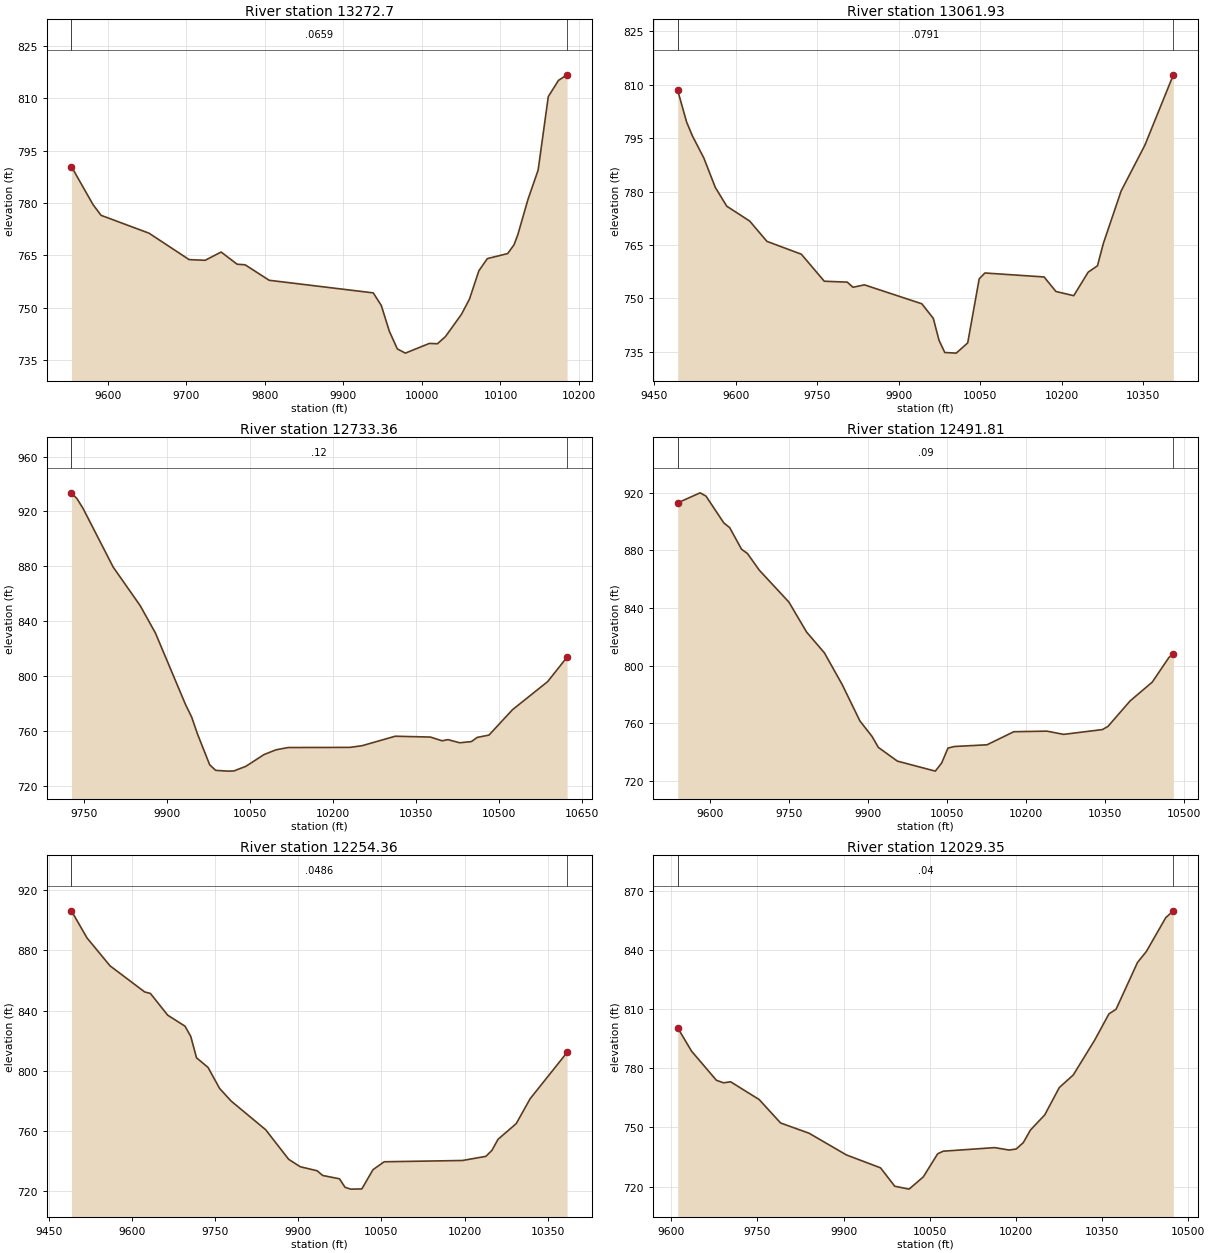
Type RM Length L Ch R = 1 , 13272.7,210.770100,210.770100,210.770100
XS GIS Cut Line= 4
478697.362552106794818.014362603478626.181996554795182.597695932
478596.668107659795326.694918171 478667.84866327795413.500473708
#Sta/Elev= 30
9553.955790.39749581.451779.52699591.639776.47269652.772771.35039703.716763.8008
9724.094763.60089744.472765.96829764.849762.48099775.038762.31339805.604757.8862
9938.082754.2797 9948.29750.68249958.497743.33719968.705738.25189978.913737.0428
10009.54739.823710019.74739.725510029.95741.769510050.37748.170710060.57 752.528
10072.51760.613910083.25764.086710109.12765.525810117.19768.026310122.05770.9202
10134.98781.026610147.91789.410910160.84810.434210173.78815.074510184.77 816.668
#Mann= 3 , 0 , 0
9553.955  0.0659       09553.955  0.0659       010184.77  0.0659       0
#XS Ineff= 2 , 0
       0                               0
Bank Sta=9553.955,10184.77
Exp/Cntr=0.3,0.1

Type RM Length L Ch R = 1 ,13061.93,328.572400,328.572400,328.572400
XS GIS Cut Line= 4
478568.890329897794729.472695947 478390.07088545795255.514362589
478410.904218823795323.222695932478673.056996554 795437.80602926
#Sta/Elev= 30
9492.755808.42629509.155799.53119519.717795.67219540.841789.43129561.965  781.16
9583.089775.87659625.337771.69539657.022765.99229720.394762.38399762.642754.7887
 9804.89754.53649815.452753.09679836.576753.76929942.196748.4541 9963.32744.3604
9973.882738.19939984.444 734.76210005.57734.583210026.69737.455410047.82755.4563
10058.28757.106710167.32755.991510189.15751.908110221.89750.728310248.48757.3385
10265.55759.117110276.46765.4412 10309.2780.169610352.85793.0211 10405.3812.7982
#Mann= 3 , 0 , 0
9492.755  0.0791       09492.755  0.0791       0 10405.3  0.0791       0
#XS Ineff= 2 , 0
       0                10083.68       0
Bank Sta=9492.755,10405.3
Exp/Cntr=0.3,0.1

Type RM Length L Ch R = 1 ,12733.36,241.548900,241.548900,241.548900
XS GIS Cut Line= 4
477865.765329927795085.375473723478225.140329897795241.625473723
478381.390329897795349.264362618478678.265329897 795453.43102926
#Sta/Elev= 30
 9727.71 933.566 9737.78929.25839748.684922.20859803.206 879.3869852.168 851.179
9879.536831.33559934.057 779.0949944.962770.11999955.866757.40689977.675735.2023
9988.579731.136510010.39730.580310021.29730.6949 10043.1734.086210075.81742.6502
10097.62746.126110119.58747.792310231.29 747.90410252.99749.100910313.15756.0352
10376.73755.429710397.93752.714610408.53753.569910429.72751.256510450.92752.1359
10461.51755.187210482.71756.8661 10525.1775.351310588.69 795.84110623.94813.7262
#Mann= 3 , 0 , 0
 9727.71    0.12       0 9727.71    0.12       010623.94    0.12       0
#XS Ineff= 2 , 0
       0                               0
Bank Sta=9727.71,10623.94
Exp/Cntr=0.3,0.1

Type RM Length L Ch R = 1 ,12491.81,237.448000,237.448000,237.448000
XS GIS Cut Line= 5
477817.154218793795621.833807036478138.334774375795456.903251499
478284.168107659 795359.68102926478376.181996584795370.097695932
478673.056996554795467.319918171
#Sta/Elev= 30
9538.087912.96439580.631919.93179591.872917.63669625.597899.06649636.838895.7544
9659.321880.77929670.562877.79989693.045866.20749749.252844.07549782.977823.2031
9816.701808.81179850.425 786.8189884.149761.5309 9907.15750.78789919.169743.1632
9955.224733.642310027.34 726.68310039.35732.328910051.37742.685910063.39743.7832
10125.57744.974410176.29754.041610239.43754.446610270.99752.201610344.65755.5423
10355.17757.707410397.26775.431210439.35788.499110470.92805.5676 10479.4808.2226
#Mann= 3 , 0 , 0
9538.087    0.09       09538.087    0.09       0 10479.4    0.09       0
#XS Ineff= 2 , 0
       0                               0
Bank Sta=9538.087,10479.4
Exp/Cntr=0.3,0.1

Type RM Length L Ch R = 1 ,12254.36,225.009100,225.009100,225.009100
XS GIS Cut Line= 4
477837.987552136795734.681029275478242.501441002795620.097695947
478417.848663241795599.264362618478688.681996554795477.736584827
#Sta/Elev= 30
 9491.12906.25389519.195888.25249560.769869.7035 9623.13852.39549633.523851.3988
9664.704836.96079695.884829.65589706.278822.88019716.671808.66819737.458802.2543
9758.245 788.3399779.032779.94569841.392760.87949882.966741.18789903.753736.2937
9934.206733.62279944.277730.48999974.488728.28329984.558722.63069994.628721.4247
10014.77721.552110034.91734.336110055.05 739.59210196.25740.443610238.46743.1895
10249.42  747.1710260.38754.490210293.26764.946810318.38781.491710384.98812.2233
#Mann= 3 , 0 , 0
 9491.12  0.0486       0 9491.12  0.0486       010384.98  0.0486       0
#XS Ineff= 2 , 0
       0                               0
Bank Sta=9491.12,10384.98
Exp/Cntr=0.3,0.1

Type RM Length L Ch R = 1 ,12029.35,203.108500,203.108500,203.108500
XS GIS Cut Line= 2
 478110.81741327796039.281723708478805.261857659795527.128945932
#Sta/Elev= 30
9611.308800.6506 9635.37788.80569678.632774.00139691.058772.69729703.483773.2103
9753.185764.17859790.461752.27499840.162747.05239904.938736.05159964.416729.4843
9989.178 720.13310014.12718.665210038.97724.911710063.82736.607710073.42737.9378
10163.22739.758710188.07738.5424 10200.5739.034910212.92 742.29110225.35748.6845
 10250.2756.361510275.59770.2752 10299.9776.671210337.18794.365110362.03 807.713
10374.45810.082710411.73833.843610427.23839.451210460.92856.607810474.18860.0924
#Mann= 3 , 0 , 0
9611.308    0.04       09611.308    0.04       010474.18    0.04       0
#XS Ineff= 2 , 0
       0                               0
Bank Sta=9611.308,10474.18
Exp/Cntr=0.3,0.1