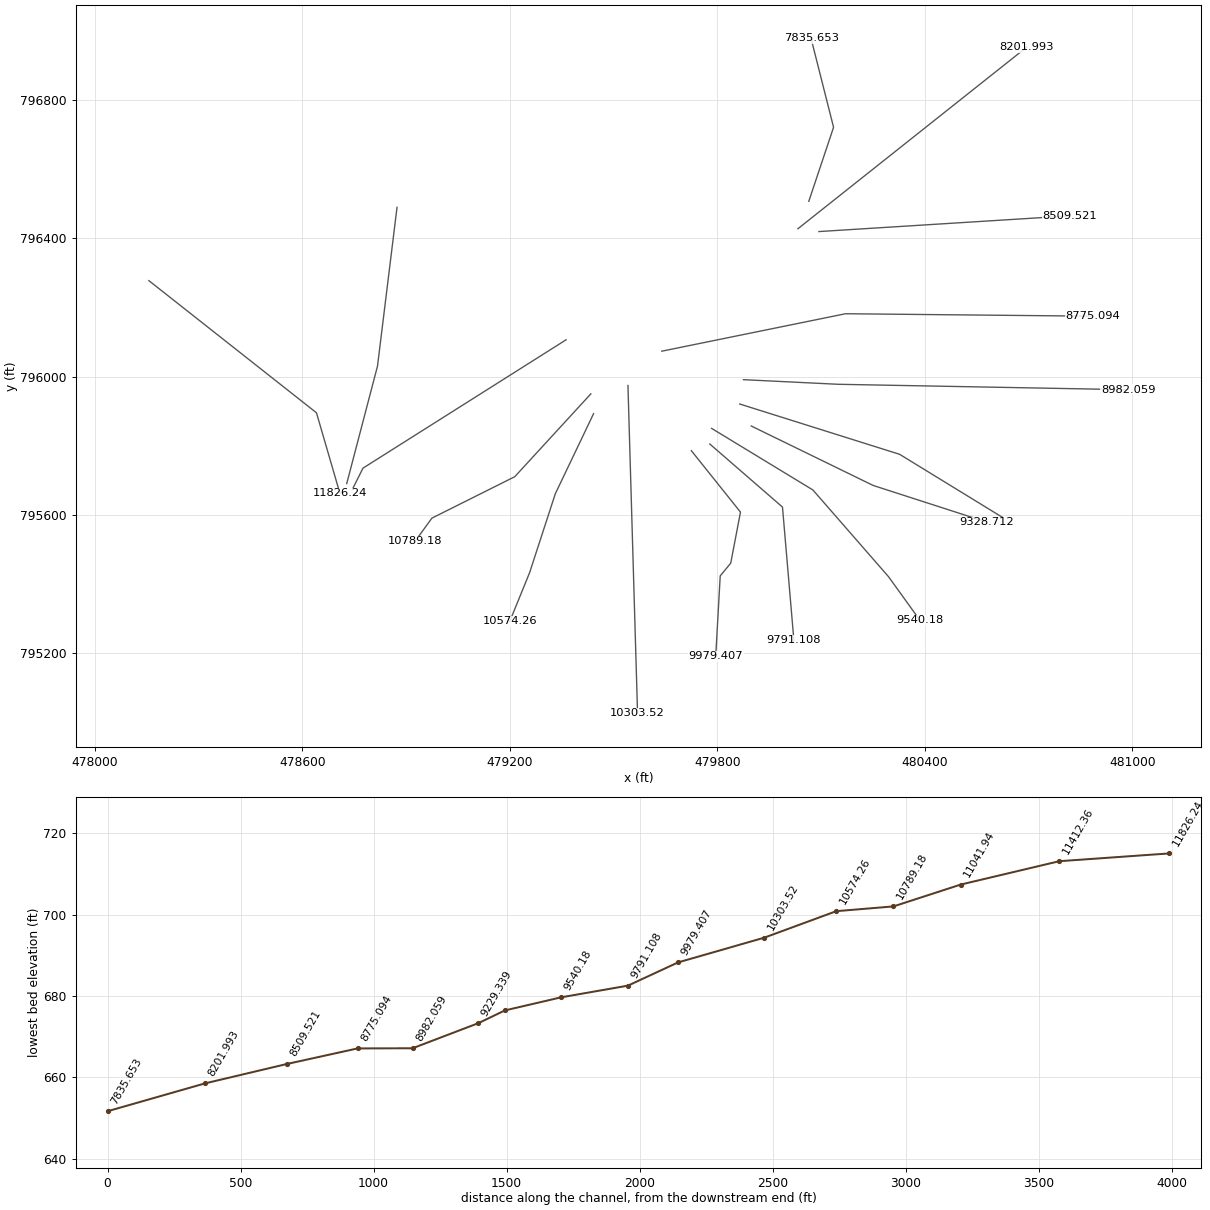
HEC-RAS study 5598_ras.prj: 5598

--- 5598_ras.g01 (geometry) --- (continued)

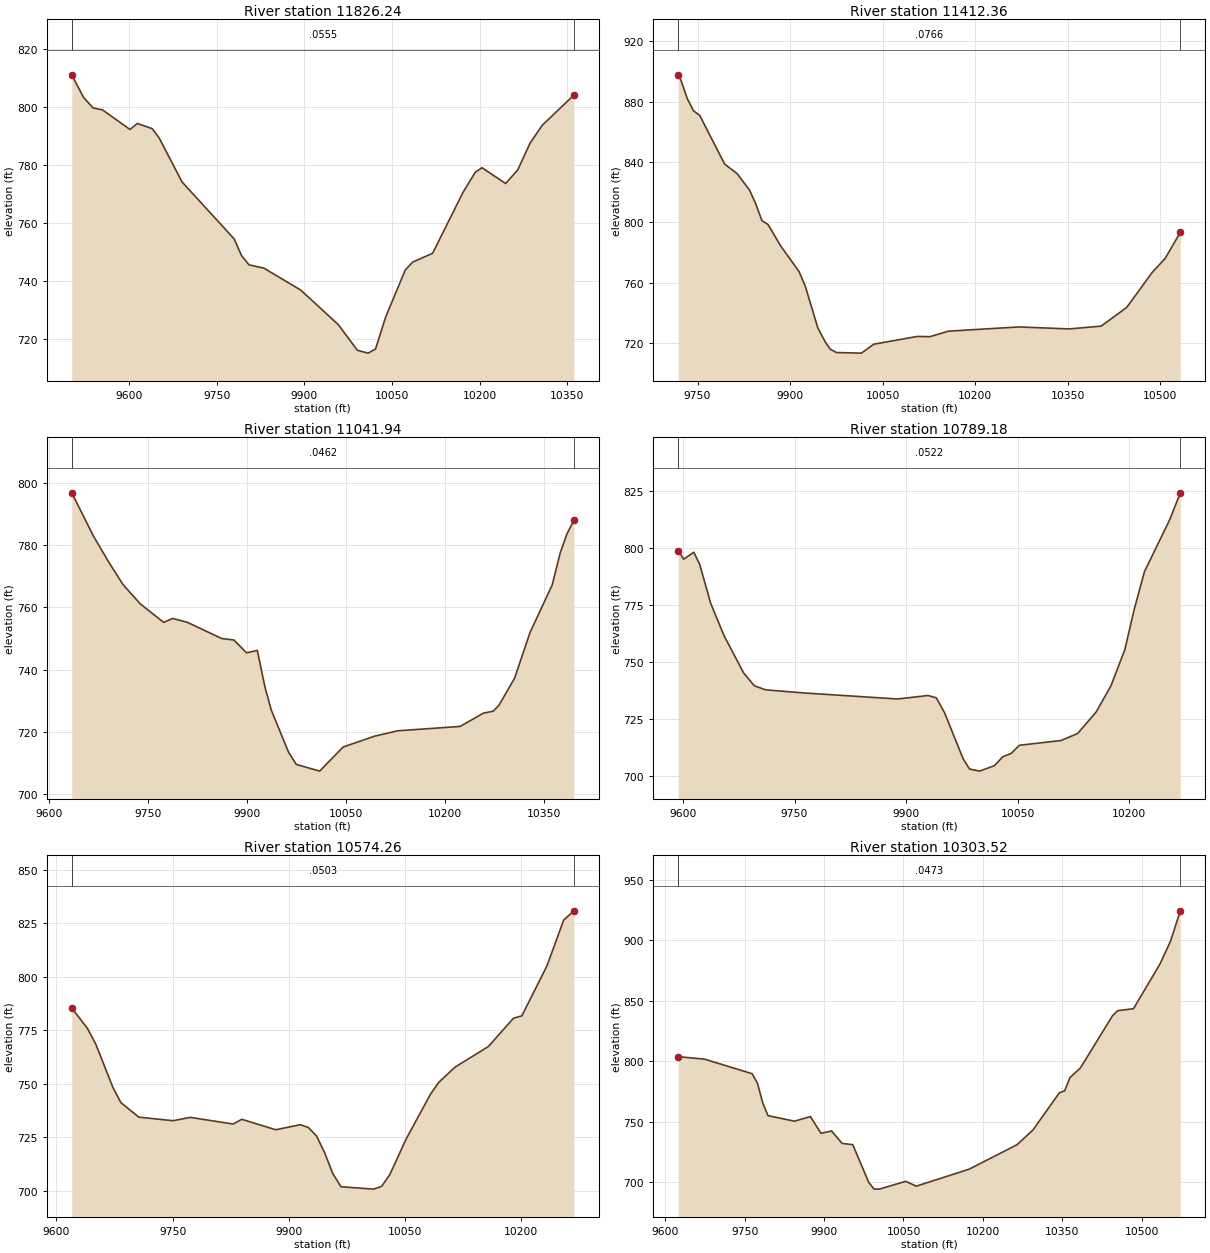
Type RM Length L Ch R = 1 ,11826.24,413.881900,413.881900,413.881900
XS GIS Cut Line= 3
478156.824357688796277.562973723478641.199357659795895.618529275
478708.907691002 795662.97964038
#Sta/Elev= 30
9501.952810.94689522.241 803.1349538.392799.54599554.542798.87919601.508 792.133
9614.243794.19179639.713 792.3979651.443 789.2219690.652 774.0529779.797754.4432
9792.532748.66989805.267745.50149830.736744.35299893.696 736.8179958.296724.8532
9990.597716.068210009.03715.091410021.76716.514610039.05727.5006 10072.7743.7739
10085.43746.464610119.44749.476910171.52770.496610192.35777.388110203.97778.9431
10244.42773.516110265.25778.250110286.08 787.37910306.91 793.54210361.09803.9656
#Mann= 3 , 0 , 0
9501.952  0.0555       09501.952  0.0555       010361.09  0.0555       0
#XS Ineff= 2 , 0
       0                               0
Bank Sta=9501.952,10361.09
Exp/Cntr=0.3,0.1

Type RM Length L Ch R = 1 ,11412.36,370.418100,370.418100,370.418100
XS GIS Cut Line= 3
 478874.09653163796489.545095995478817.672920525 796030.56072098
478728.697226077795690.933984861
#Sta/Elev= 30
9718.759897.78219723.339 894.0079733.414882.01999743.489 873.9279753.565870.8892
9793.866838.63979814.016832.30639834.167821.39649844.242812.33999854.317801.0795
9864.393798.44349884.543  784.439914.769 767.1159924.844 757.3099944.995729.8343
 9957.23720.46659965.145715.77339975.221713.565310015.52713.175510035.67719.0899
 10106.2724.260610126.35724.068510156.58727.737610270.66730.546310352.35729.2244
10404.03731.094110445.38743.458310486.73766.703810507.42775.804910532.29793.2617
#Mann= 3 , 0 , 0
9718.759  0.0766       09718.759  0.0766       010532.29  0.0766       0
#XS Ineff= 2 , 0
       0                               0
Bank Sta=9718.759,10532.29
Exp/Cntr=0.3,0.1

Type RM Length L Ch R = 1 ,11041.94,252.764700,252.764700,252.764700
XS GIS Cut Line= 3
479362.900746554796106.642834827 478775.66116327795735.549084827
478745.713246584795675.653251499
#Sta/Elev= 30
9634.284796.72859667.289782.80579690.947774.31099712.237767.23639738.265761.0851
9773.753755.14969787.115756.41479809.241755.21729861.992749.95629880.217749.5121
9899.431745.38239915.705746.16589927.534 734.265 9936.87727.05199963.022713.5645
9974.852709.583310010.34707.429510045.83715.157810093.15718.615610128.63720.3712
10223.27721.764910258.76726.032510273.82726.674710282.41728.598510306.07737.2613
10329.56751.9587 10363.1767.179210375.15777.390210385.47 783.55110395.92787.8814
#Mann= 3 , 0 , 0
9634.284  0.0462       09634.284  0.0462       010395.92  0.0462       0
#XS Ineff= 2 , 0
       0                               0
Bank Sta=9634.284,10395.92
Exp/Cntr=0.3,0.1

Type RM Length L Ch R = 1 ,10789.18,214.916300,214.916300,214.916300
XS GIS Cut Line= 4
479434.515329897795950.392834842479214.463246554795710.809501484
478974.879913241795591.017834812478926.702829927795524.611584827
#Sta/Elev= 30
9593.597 798.839 9600.92795.06089614.498798.11529622.447792.8487 9637.23775.6874
9655.231761.47959681.579745.13659695.965739.49929711.145737.72969763.855  736.33
9888.542733.71459929.482735.24549940.663734.21949951.843727.63479976.614707.5642
9985.384702.97829998.974702.057210018.92704.480210030.11708.367210041.29709.8244
10052.47713.404310108.37715.498510130.73718.5578 10155.5727.958210175.45739.4173
 10194.2755.375610206.55772.660110220.62789.622810254.68812.445610268.81824.1755
#Mann= 3 , 0 , 0
9593.597  0.0522       09593.597  0.0522       010268.81  0.0522       0
#XS Ineff= 2 , 0
       0                               0
Bank Sta=9593.597,10268.81
Exp/Cntr=0.3,0.1

Type RM Length L Ch R = 1 ,10574.26,270.743700,270.743700,270.743700
XS GIS Cut Line= 4
479442.327829897795893.101168171479331.650746554795661.330334842
479257.431996584795433.465751499479200.140329897795292.840751499
#Sta/Elev= 30
9619.767785.46819639.826776.04859650.908768.48929673.071748.23619683.185741.3022
9706.316734.51259750.643732.83989772.806734.40319828.215731.28589839.296733.4997
9883.266728.61229914.817730.98379925.334729.66689935.851725.71319946.368717.8199
9956.885708.11049967.402702.012510009.47700.885610019.99702.2159 10030.5707.7145
10051.54724.282410083.09745.288510093.61750.738910114.64757.844610157.79767.5172
10190.18780.715410200.98 781.81310233.38805.159810254.97826.5289 10268.1830.8603
#Mann= 3 , 0 , 0
9619.767  0.0503       09619.767  0.0503       0 10268.1  0.0503       0
#XS Ineff= 2 , 0
       0                               0
Bank Sta=9619.767,10268.1
Exp/Cntr=0.3,0.1

Type RM Length L Ch R = 1 ,10303.52,324.112900,324.112900,324.112900
XS GIS Cut Line= 2
479541.720191002 795974.52477926479569.497968793795026.608112618
#Sta/Elev= 30
9624.585803.78369674.131801.80049764.169789.74479774.174781.98769784.178 765.618
9794.182755.07119844.204 750.5079874.217754.32819894.225740.50999914.234742.3835
9934.242732.13189954.251731.11399984.264700.08759994.268694.458310004.27694.3658
10054.29 700.794 10074.3696.810710174.35710.896610264.38731.0242 10294.4743.1224
10344.42773.939510354.42775.620610364.43786.486110384.44 794.61210444.46837.3998
10454.47841.828410484.48 843.469 10534.5  880.3710554.51899.381110572.91924.3372
#Mann= 3 , 0 , 0
9624.585  0.0473       09624.585  0.0473       010572.91  0.0473       0
#XS Ineff= 2 , 0
       0                               0
Bank Sta=9624.585,10572.91
Exp/Cntr=0.3,0.1

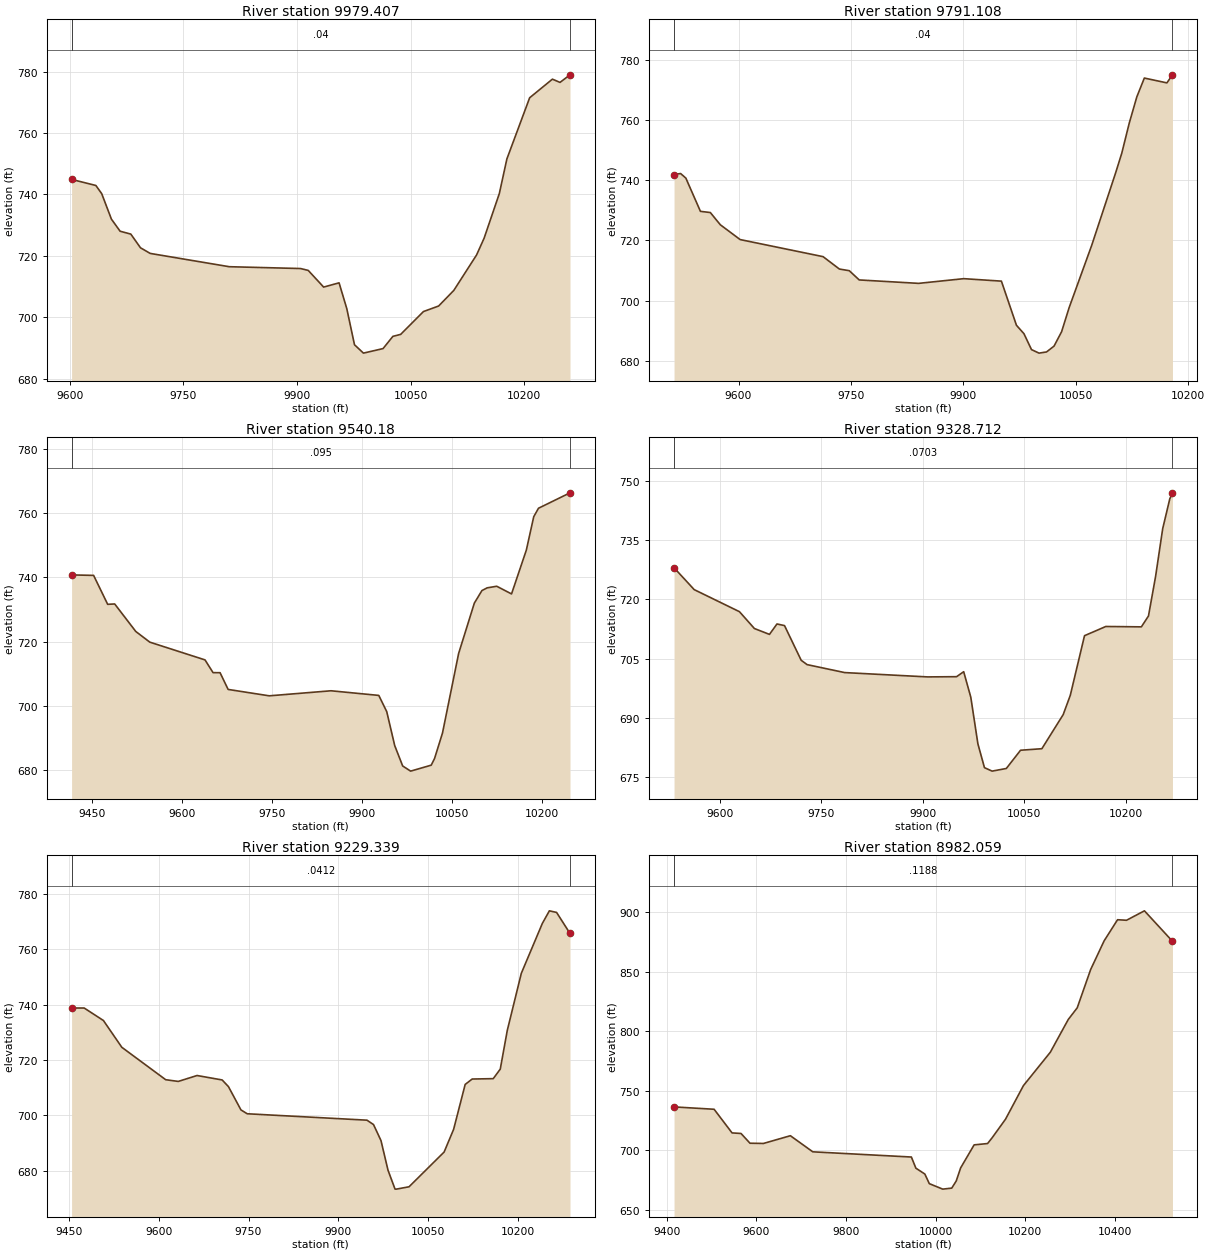
Type RM Length L Ch R = 1 ,9979.407,188.298600,188.298600,188.298600
XS GIS Cut Line= 5
479724.966897897795786.064560016479867.043580234795608.468707085
479838.831774682795460.899262652479808.449830264795424.006901532
479795.428996921795191.802040428
#Sta/Elev= 30
9602.502744.86929634.571742.88469642.284740.21499655.091731.91869666.586727.9839
9680.703727.04979693.509722.57989706.316720.75519810.657716.42529904.735715.8306
9914.916715.22129935.278709.78979955.641711.17319965.822702.78159976.003691.0053
 9987.82688.275310013.73689.757910026.68693.734110036.99 694.38410067.04701.8167
10087.07703.6224 10107.1708.699910137.15720.241410147.16725.7324 10167.2740.2356
10177.21751.543810207.26771.461810237.31777.520110247.32776.463710260.54778.9315
#Mann= 3 , 0 , 0
9602.502    0.04       09602.502    0.04       010260.54    0.04       0
#XS Ineff= 2 , 0
       0                               0
Bank Sta=9602.502,10260.54
Exp/Cntr=0.3,0.1

Type RM Length L Ch R = 1 ,9791.108,250.927900,250.927900,250.927900
XS GIS Cut Line= 3
479778.403990507795805.317713499479988.473434955795623.026046827
480021.459546059795237.609380156
#Sta/Elev= 30
9513.958741.85189522.691742.1989  9529.7740.68069549.171729.63979562.411 729.239
9575.652725.19499602.132720.26869712.793714.59779734.534710.48519747.774709.9312
9761.014706.86439840.295705.72889900.514707.28829950.697706.4675 9970.77691.8169
9980.807689.00489990.843683.735610000.88 682.56510010.92682.958710020.95684.9017
10030.99689.666210041.03697.646710071.14718.333510103.17742.482210111.28748.9452
10121.32 758.98410131.36767.649710141.39773.8936 10171.5772.293310178.92774.9674
#Mann= 3 , 0 , 0
9513.958    0.04       09513.958    0.04       010178.92    0.04       0
#XS Ineff= 2 , 0
       0                               0
Bank Sta=9513.958,10178.92
Exp/Cntr=0.3,0.1

Type RM Length L Ch R = 1 , 9540.18,211.468700,211.468700,211.468700
XS GIS Cut Line= 4
 479783.63307376795850.501179407480076.442413241795672.441445932
 480295.19241327795421.573390394480385.706774682795295.968707085
#Sta/Elev= 30
 9416.24740.79289452.952740.64089476.359731.63589488.063731.74489523.175723.1846
9546.582 719.8519638.537714.32749651.917 710.3599663.621710.3415 9677.03705.1327
9745.547703.14119848.419704.71249928.026703.26949941.293698.21199954.561687.6473
9967.829681.29769981.097679.693410015.41681.5529 10020.9683.604510034.17691.5634
10061.06716.337710087.24732.021910099.89735.920510108.56736.762510124.54737.2598
10149.19734.868510173.84748.515910186.17758.912810194.08 761.54910246.61766.3514
#Mann= 3 , 0 , 0
 9416.24   0.095       0 9416.24   0.095       010246.61   0.095       0
#XS Ineff= 2 , 0
       0                               0
Bank Sta=9416.24,10246.61
Exp/Cntr=0.3,0.1

Type RM Length L Ch R = 1 ,9328.712,99.372600,99.372600,99.372600
XS GIS Cut Line= 3
479898.195657164795857.401046827480250.626212716795685.526046827
480578.751212716795579.623269051
#Sta/Elev= 30
9532.408728.0049 9562.23722.4553 9629.14716.86599651.237712.59789673.488711.1188
9684.614713.7558 9695.74713.34259720.394704.55289729.117703.45589784.746701.4369
 9907.13700.34239950.128700.39739960.635701.66089971.143695.20169981.651 683.377
9991.343677.348910002.67676.468410023.68677.1417 10044.7681.760110076.22682.1485
10107.75  690.7910118.25695.675110139.27710.786710170.79713.119110223.33713.0231
10233.84715.778210244.35725.792410254.86737.903110265.37745.473210269.31746.9847
#Mann= 3 , 0 , 0
9532.408  0.0703       09532.408  0.0703       010269.31  0.0703       0
#XS Ineff= 2 , 0
       0                               0
Bank Sta=9532.408,10269.31
Exp/Cntr=0.3,0.1

Type RM Length L Ch R = 1 ,9229.339,247.279900,247.279900,247.279900
XS GIS Cut Line= 3
479864.873441398795920.968707085480327.113024682795775.569401547
480624.422052503795593.277734876
#Sta/Elev= 30
9454.141738.7866 9475.24738.7776 9507.36734.26749538.138724.5902 9611.52712.8752
9632.486 712.2619663.935714.39479705.867  712.79 9716.35710.40069737.316701.9624
  9747.8700.57369947.961698.2588 9958.93696.66979971.421690.88769983.151680.1941
9994.881673.36329997.192673.344910018.34 674.19510076.99686.751910092.85694.9457
10112.18711.175510123.91713.1246 10159.1713.260310170.83716.708210182.56730.6787
10206.02751.318610241.21769.353710252.94 773.89810265.03773.313610287.45765.7121
#Mann= 3 , 0 , 0
9454.141  0.0412       09454.141  0.0412       010287.45  0.0412       0
#XS Ineff= 2 , 0
       0                               0
Bank Sta=9454.141,10287.45
Exp/Cntr=0.3,0.1

Type RM Length L Ch R = 1 ,8982.059,206.965400,206.965400,206.965400
XS GIS Cut Line= 3
479875.694796097795991.346478749480149.359079897795977.997001499
480987.541602452795962.330038464
#Sta/Elev= 30
 9416.27736.27519505.681734.29899545.729714.42479565.752713.94129585.776705.7453
9615.812705.56219675.883712.06469725.906698.52669945.945 694.1479955.947 684.786
 9975.95679.85899985.952671.765710015.96667.169110035.96 668.01910045.96673.9665
10055.96685.073610085.97704.369410115.97705.488110125.98710.250610155.98725.9288
10195.99754.1745   10256782.237310296.01809.746710316.01 819.54610346.01851.7401
10376.02875.814310406.03893.606210426.03893.153610466.04  901.0910528.59875.5103
#Mann= 3 , 0 , 0
 9416.27  0.1188       0 9416.27  0.1188       010528.59  0.1188       0
#XS Ineff= 2 , 0
       0                               0
Bank Sta=9416.27,10528.59
Exp/Cntr=0.3,0.1

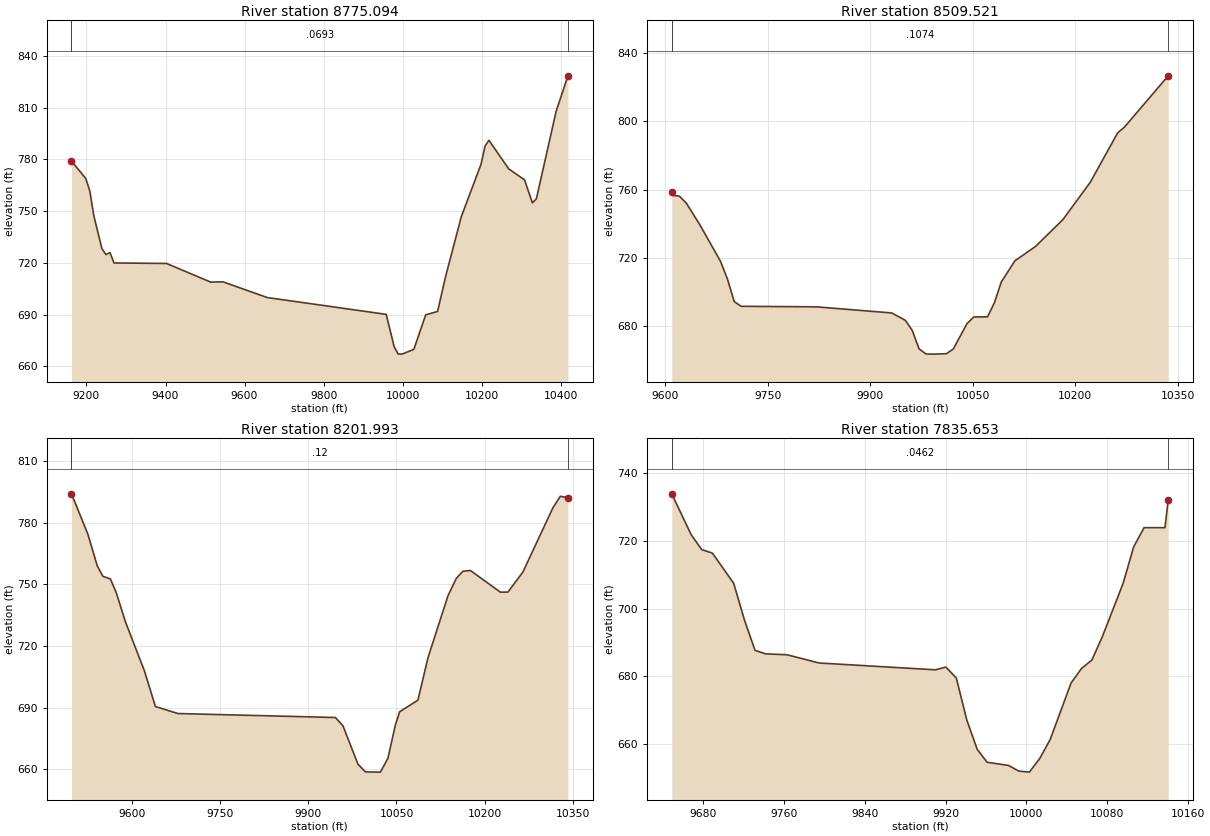
Type RM Length L Ch R = 1 ,8775.094,265.572500,265.572500,265.572500
XS GIS Cut Line= 3
479639.546177357796073.688181162 480170.78539905 796181.97996524
 480884.83871913  796174.8749571
#Sta/Elev= 30
9162.082778.95999198.265768.90279208.471 761.6499218.676747.22939239.088728.2466
9249.293724.82699259.499725.96519269.705719.95129402.378719.6684 9514.64708.8408
9545.257709.0312 9657.52699.90969958.474690.16749978.475671.54049988.475667.2216
9998.476667.124310028.48669.897110058.48  689.9210088.48691.848910108.48711.8269
10148.48 746.72110198.49777.180910208.49787.629710218.49791.041710268.49774.4819
10308.49768.103310328.49754.741410338.49757.138510388.49807.821410418.34828.3922
#Mann= 3 , 0 , 0
9162.082  0.0693       09162.082  0.0693       010418.34  0.0693       0
#XS Ineff= 2 , 0
       09676.488                       0
Bank Sta=9162.082,10418.34
Exp/Cntr=0.3,0.1

Type RM Length L Ch R = 1 ,8509.521,307.528000,307.528000,307.528000
XS GIS Cut Line= 2
480093.784323175796419.524700059480818.834126946 796464.95863032
#Sta/Elev= 30
9609.382758.4309  9610.6756.57699620.619756.10679630.639752.06379650.678739.1922
9680.737717.81369690.757707.56569700.776694.19719710.796691.40489821.012691.0816
9931.227687.49629951.267683.15519961.286677.25959971.306666.36769981.325663.4122
9991.345663.296610011.38663.5493 10021.4666.325510041.44681.227310051.46685.1493
 10071.5685.228110081.52693.462510091.54 705.63710111.58718.156110141.64 726.558
10181.72742.3116 10221.8  764.2610261.87793.299510271.89796.722610335.85826.8283
#Mann= 3 , 0 , 0
9609.382  0.1074       09609.382  0.1074       010335.85  0.1074       0
#XS Ineff= 2 , 0
       0                               0
Bank Sta=9609.382,10335.85
Exp/Cntr=0.3,0.1

Type RM Length L Ch R = 1 ,8201.993,366.340000,366.340000,366.340000
XS GIS Cut Line= 2
480033.126441002796427.736584857480695.032611653796953.070820841
#Sta/Elev= 30
9496.782794.07619524.708774.42039540.638758.99439550.241753.90199563.008752.6348
9572.809746.09569588.542731.78849621.067707.73589639.609690.49189677.909687.0618
9946.012685.13189958.868681.10239984.312662.45069997.079658.647810022.61658.5283
10035.38665.247410048.15681.539410055.38687.953110086.45693.562510103.64714.2747
10137.51744.3287 10151.9752.966910163.05756.350310175.81756.747310226.88746.1729
10239.65  746.2210265.18755.980810316.25787.265710328.84792.885410341.82792.2066
#Mann= 3 , 0 , 0
9496.782    0.12       09496.782    0.12       010341.82    0.12       0
#XS Ineff= 2 , 0
       0                               0
Bank Sta=9496.782,10341.82
Exp/Cntr=0.3,0.1

Type RM Length L Ch R = 1 ,7835.653,236.554900,236.554900,236.554900
XS GIS Cut Line= 3
 480064.52621913  796506.9062071480136.140802473 796720.99040848
480071.036635846796978.151866809
#Sta/Elev= 30
9649.191733.89319668.271721.88859678.815717.4134 9689.36716.38819710.449707.4729
9720.994696.70419731.539687.64799742.083686.61469763.173686.35369794.807683.9236
9910.019681.90359920.334 682.708 9930.65679.46549940.965667.12919951.281658.4273
9961.077654.59089982.227653.65969992.542651.974710002.86 651.67910013.17655.7116
10023.49661.323610044.12677.991210054.44682.297110064.75684.811510075.07 691.703
 10095.7707.516310106.01718.198810116.33 723.89410136.96723.897610140.21731.9244
#Mann= 3 , 0 , 0
9649.191  0.0462       09649.191  0.0462       010140.21  0.0462       0
#XS Ineff= 2 , 0
       0                               0
Bank Sta=9649.191,10140.21
Exp/Cntr=0.3,0.1