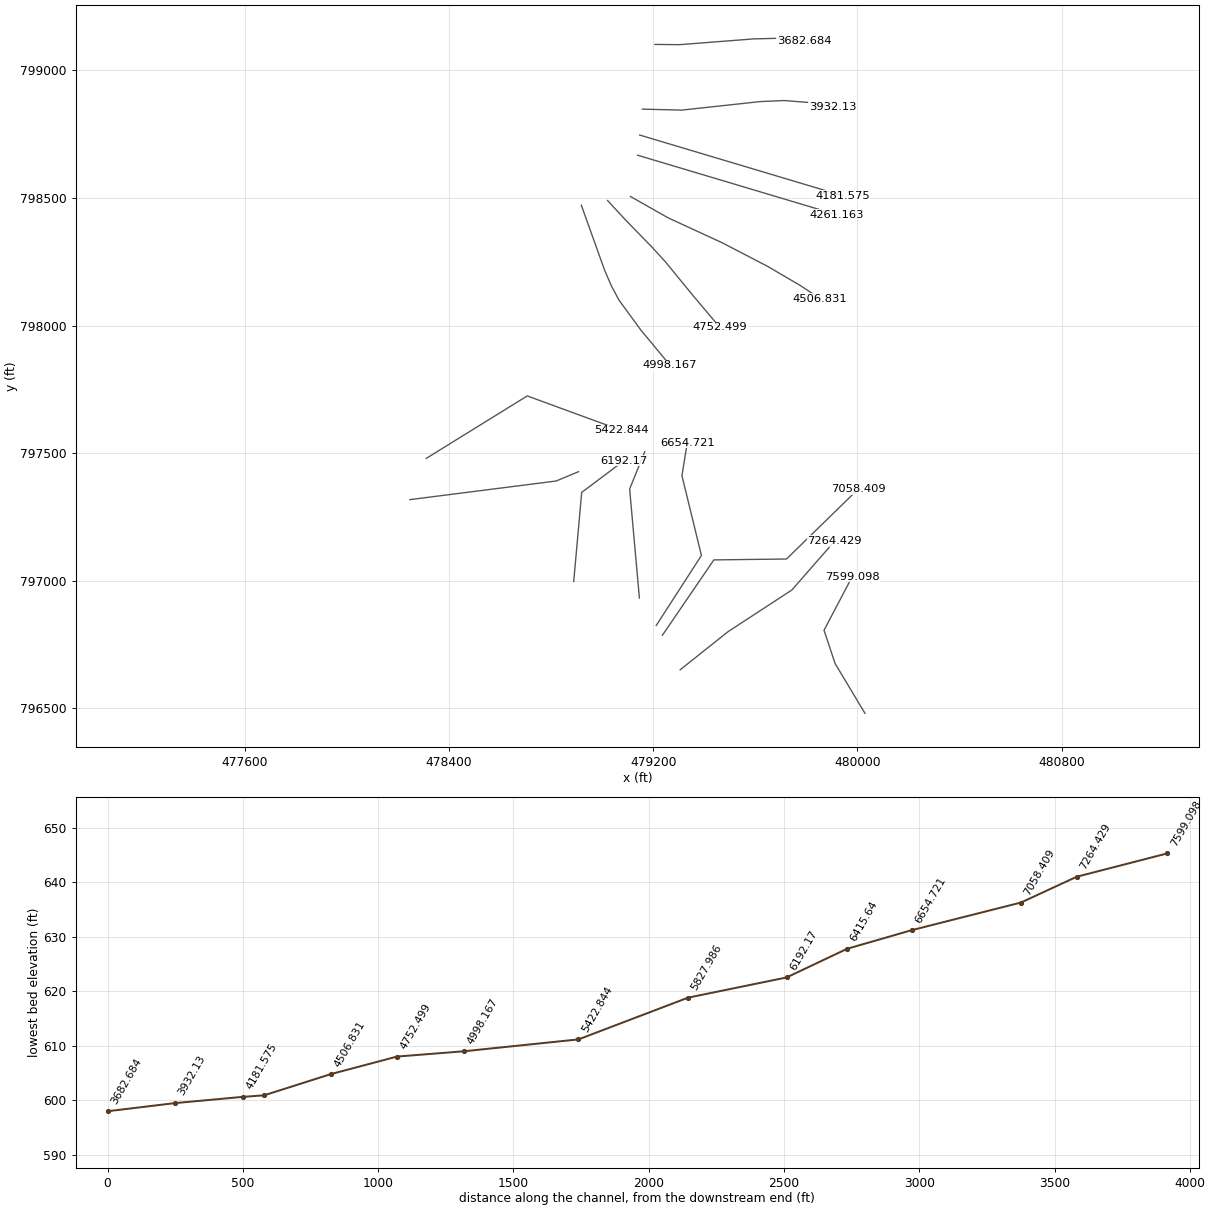
HEC-RAS study 5598_ras.prj: 5598

--- 5598_ras.g01 (geometry) --- (continued)

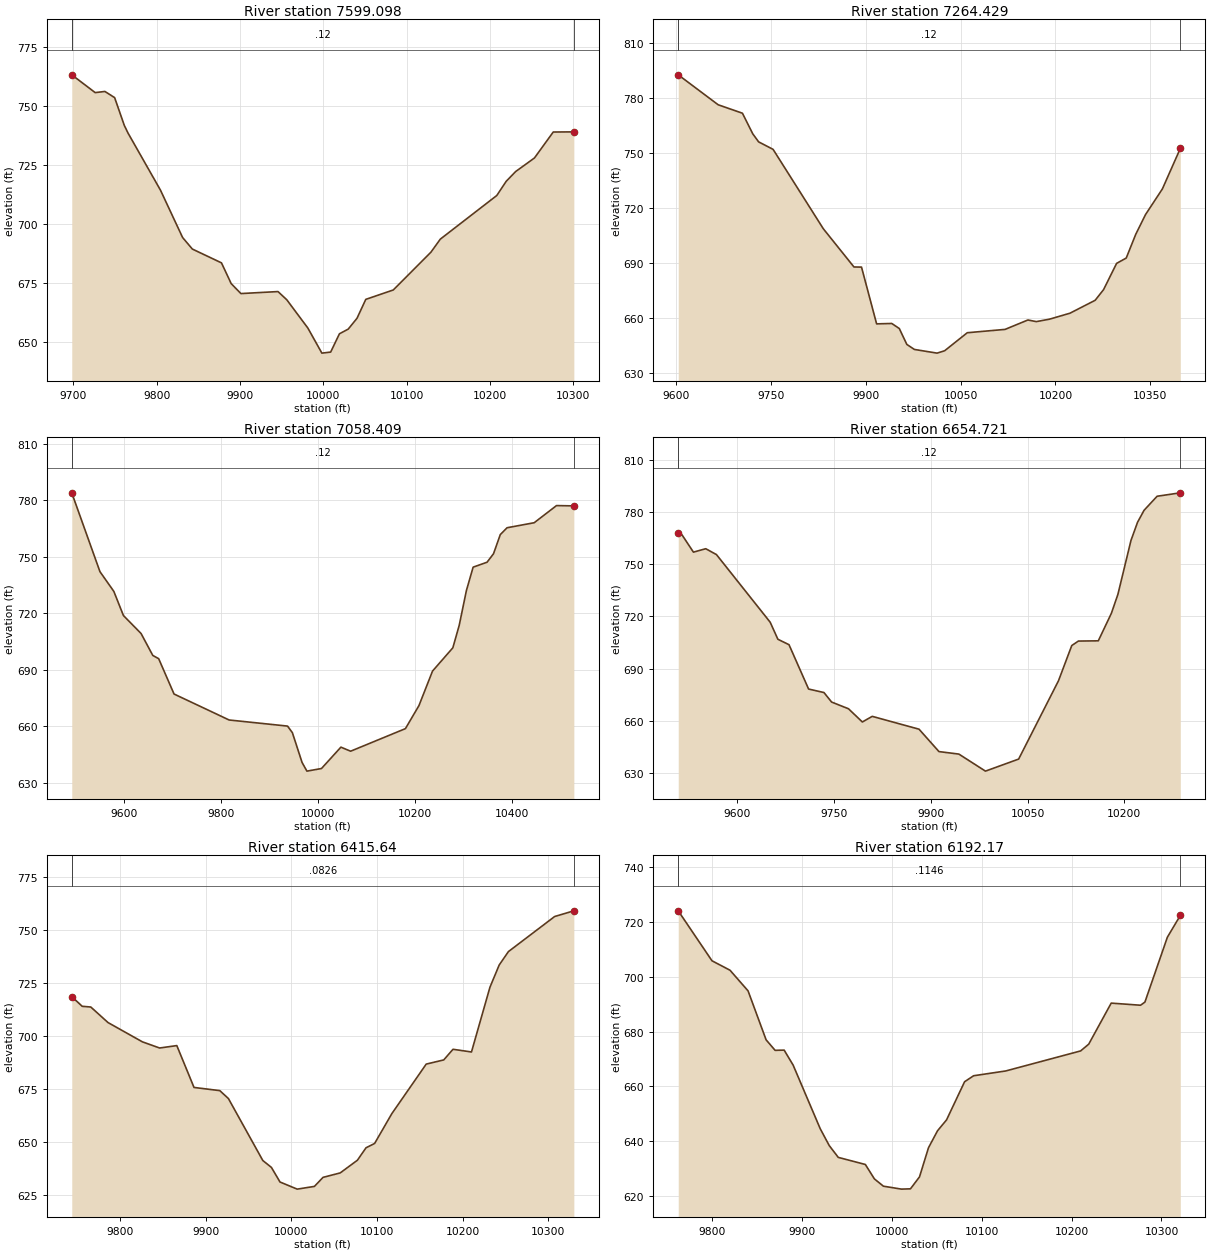
Type RM Length L Ch R = 1 ,7599.098,334.668900,334.668900,334.668900
XS GIS Cut Line= 4
480029.803996921796480.864540428479912.616496921796676.177040428
 479869.21371913796806.385373756479979.890802473 797016.88884598
#Sta/Elev= 30
9697.994763.17059726.141755.63899737.802756.12659749.464753.52029761.126 741.707
9765.641 738.4459804.514714.33119831.098694.2713 9842.76   689.49877.745683.5488
9889.407674.76799901.069670.54689945.607671.39439956.148667.93059981.474655.9501
9998.311645.328710008.85645.769710019.39653.519710029.93655.497310040.48660.0832
10051.02668.087610084.05672.073710129.24688.074310140.54693.604310208.33712.0771
10219.62718.083610230.92 722.19910253.52727.953910276.11738.952910300.84 739.013
#Mann= 3 , 0 , 0
9697.994    0.12       09697.994    0.12       010300.84    0.12       0
#XS Ineff= 2 , 0
       0                               0
Bank Sta=9697.994,10300.84
Exp/Cntr=0.3,0.1

Type RM Length L Ch R = 1 ,7264.429,206.020100,206.020100,206.020100
XS GIS Cut Line= 4
479305.609079897796651.608112603479493.109079927796800.913668171
479743.109079927796964.108112603479911.286897619797156.311332835
#Sta/Elev= 30
9603.679792.59439666.816776.28569705.166771.68699721.497760.47049730.732756.0924
9753.604752.00889832.997 708.7719881.448687.9526 9893.39687.88489917.274656.9674
9941.158657.1896  9953.1654.44059965.042645.77199976.984643.042110012.81 641.038
10024.75642.320810060.58652.144910120.29653.958910156.39659.082610169.67658.1964
10190.34659.509110222.83662.767510262.69669.804510275.98   675.610296.64689.9215
10311.83692.817110327.02705.852610342.41716.534610368.99730.468210397.31752.4961
#Mann= 3 , 0 , 0
9603.679    0.12       09603.679    0.12       010397.31    0.12       0
#XS Ineff= 2 , 0
       0                               0
Bank Sta=9603.679,10397.31
Exp/Cntr=0.3,0.1

Type RM Length L Ch R = 1 ,7058.409,403.688700,403.688700,403.688700
XS GIS Cut Line= 4
479236.164635479796787.024779275479437.553524345797082.163668171
479722.275746554 797085.63589038480003.525746584797359.941445947
#Sta/Elev= 30
9492.934783.88749551.013742.09269579.577731.64749599.438718.81179635.757709.2937
9659.969697.65679672.076695.9373 9703.77677.1867 9817.35663.41939937.688660.1861
9947.689 656.692 9967.69640.86669977.691636.303910007.69637.6924 10047.7649.0194
 10067.7646.865810180.69658.837910208.63 671.07810236.56 689.35910278.47 701.711
10291.61713.666910306.41732.098510320.26744.4699 10348.9747.080710362.28751.5857
10376.25761.739810390.22 765.36610446.09768.027410492.12777.119910527.85776.9585
#Mann= 3 , 0 , 0
9492.934    0.12       09492.934    0.12       010527.85    0.12       0
#XS Ineff= 2 , 0
       0                               0
Bank Sta=9492.934,10527.85
Exp/Cntr=0.3,0.1

Type RM Length L Ch R = 1 ,6654.721,239.080700,239.080700,239.080700
XS GIS Cut Line= 4
479211.859079897796825.219223723479388.942413241 797099.52477926
479312.553524345797412.024779275479333.386857688797540.497001484
#Sta/Elev= 30
9508.443767.81029514.234766.85919531.988756.9069 9551.11 758.8669567.696755.4975
9651.016716.67439662.918706.90539680.173703.7858 9710.53678.33339734.335676.3329
9746.238670.86259772.361667.02539793.849659.43949809.236662.65469881.757655.2874
 9912.64642.44069943.524641.00269984.701631.225910036.17638.143810097.94683.0815
10118.53703.312310128.82705.866710159.66706.006810179.92721.794410190.05732.6901
10210.31763.620810220.44773.996410230.57780.901210250.83788.978810286.79790.9432
#Mann= 3 , 0 , 0
9508.443    0.12       09508.443    0.12       010286.79    0.12       0
#XS Ineff= 2 , 0
       0                               0
Bank Sta=9508.443,10286.79
Exp/Cntr=0.3,0.1

Type RM Length L Ch R = 1 , 6415.64,223.469700,223.469700,223.469700
XS GIS Cut Line= 3
479145.886857688796932.858112603 479107.69241327797359.941445947
479166.720191032797505.774779275
#Sta/Elev= 30
9743.698718.50469755.888713.94199765.928   713.69786.008706.28619826.167697.1949
9846.247694.29249866.327695.43099886.407675.71039916.526674.20819926.566670.4836
9966.726 641.2839976.766638.02699986.806631.147810006.89627.800510026.97629.0839
10037.01633.340210057.09635.440610077.16641.4211 10087.2647.278610097.24649.3216
10117.32 663.35710157.48686.711610177.94688.677910188.73693.688710210.31692.4202
10231.88722.945110242.67733.398510253.46739.7233 10307.4756.247310329.81758.9282
#Mann= 3 , 0 , 0
9743.698  0.0826       09743.698  0.0826       010329.81  0.0826       0
#XS Ineff= 2 , 0
       0                               0
Bank Sta=9743.698,10329.81
Exp/Cntr=0.3,0.1

Type RM Length L Ch R = 1 , 6192.17,364.184600,364.184600,364.184600
XS GIS Cut Line= 3
478888.595191002796997.615057051478919.845191002 797346.57339038
479086.511857659797471.573390394
#Sta/Elev= 30
9762.275724.0528 9799.81705.8359 9819.89702.3883 9839.97694.8608 9860.05 676.998
 9870.09673.1594 9880.13673.2453 9890.17667.7494 9920.29644.5596 9930.33638.4144
 9940.37634.1113 9970.49631.5263 9980.53626.2793 9990.57623.609910010.65 622.536
10020.69622.647610030.73626.999210040.77637.646710050.81643.823510060.85647.7958
10080.93661.712810090.97663.891710126.67665.637710210.01672.946610219.07675.4248
10244.07690.387210276.67689.614610281.57690.757710306.57714.428310320.96 722.362
#Mann= 3 , 0 , 0
9762.275  0.1146       09762.275  0.1146       010320.96  0.1146       0
#XS Ineff= 2 , 0
       0                               0
Bank Sta=9762.275,10320.96
Exp/Cntr=0.3,0.1

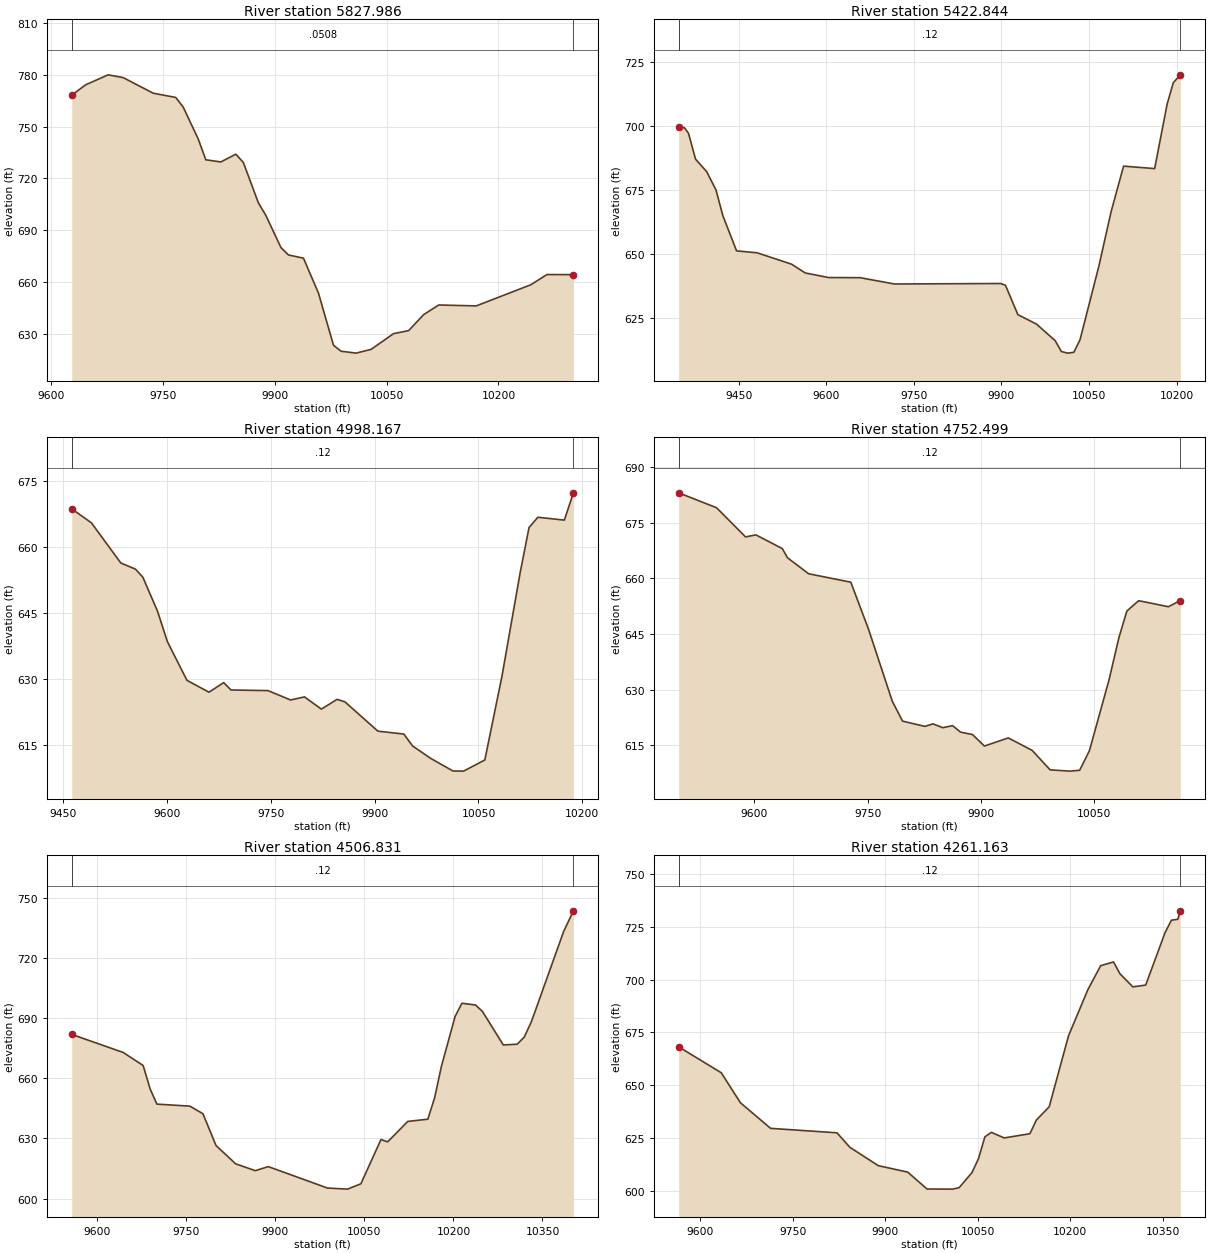
Type RM Length L Ch R = 1 ,5827.986,405.141700,405.141700,405.141700
XS GIS Cut Line= 3
478246.581302106 797318.27477926478819.497968823797391.191445947
478907.773338289797427.859676342
#Sta/Elev= 30
9627.515768.24969646.082774.22899676.324780.04629696.486778.44059736.808769.4038
 9767.05766.94169777.131761.30979797.292742.80899807.373730.83019827.534729.5679
9847.696734.09139857.776729.26569877.938705.89869888.018698.5774 9908.18680.0251
 9918.26675.69499938.422673.83679958.583653.55449978.744623.37879988.825619.9322
10008.99618.821410029.15620.987610059.39630.123710079.55631.858710099.71641.1318
10119.87646.710110170.28646.1774 10243.5658.428810265.15664.346510300.64664.2884
#Mann= 3 , 0 , 0
9627.515  0.0508       09627.515  0.0508       010300.64  0.0508       0
#XS Ineff= 2 , 0
       0                               0
Bank Sta=9627.515,10300.64
Exp/Cntr=0.3,0.1

Type RM Length L Ch R = 1 ,5422.844,424.676400,424.676400,424.676400
XS GIS Cut Line= 3
478310.648904324 797479.77947098478706.482237667797724.571137652
479076.273904353 797589.15447098
#Sta/Elev= 30
9347.282699.53549357.208699.24059364.156697.0472 9376.22686.95899395.233682.0706
9411.187674.95599422.944664.8954 9446.46651.11499481.733650.36039540.522645.9306
9564.037642.4877 9604.37640.68489658.099640.63539716.888638.17689898.689638.3575
9906.959637.69269928.258626.18949960.206622.49399992.154616.0076 10002.8611.7727
10013.45611.1533 10024.1611.470410034.75616.4131 10066.7644.8912   10088666.4795
 10109.3684.227410162.54683.272810183.84708.418910194.49716.8545 10206.5719.9178
#Mann= 3 , 0 , 0
9347.282    0.12       09347.282    0.12       0 10206.5    0.12       0
#XS Ineff= 2 , 0
       0                               0
Bank Sta=9347.282,10206.5
Exp/Cntr=0.3,0.1

Type RM Length L Ch R = 1 ,4998.167,245.668200,245.668200,245.668200
XS GIS Cut Line= 6
478918.390923069798471.759610713479009.502298067798217.490109602
 479035.74608797798156.539035928479065.642811018798100.474846037
479150.351939893797984.280870573479266.000844467797844.723731716
#Sta/Elev= 30
9462.082668.71859490.508665.53079532.999656.38479554.244654.97659564.866653.1436
9586.112645.37949600.255638.49169628.602629.6529 9660.47626.94859681.715629.1361
9692.338627.45369745.782627.30779778.444625.17039798.544625.87579822.954623.0945
 9845.62625.31169856.953624.74989904.645618.0716 9942.11617.4097 9954.77614.7057
9980.312611.930510013.12608.9953 10028.5608.964710059.25611.508710084.01630.6096
10110.34654.223210123.14  664.47 10135.9666.801510174.15666.148510187.26672.3661
#Mann= 3 , 0 , 0
9462.082    0.12       09462.082    0.12       010187.26    0.12       0
#XS Ineff= 2 , 0
       0                               0
Bank Sta=9462.082,10187.26
Exp/Cntr=0.3,0.1

Type RM Length L Ch R = 1 ,4752.499,245.668200,245.668200,245.668200
XS GIS Cut Line= 6
479021.275504042798490.050202892479089.045838872798416.663517706
479194.559507216798308.201950754479247.635221547798250.279579164
479354.761680738 798119.22198951 479461.11033911797993.317055481
#Sta/Elev= 30
9499.944683.09279550.066679.07439588.425671.20249602.171 671.7429637.071668.0506
9644.025665.55859671.928661.25659727.733658.98199751.168646.31299782.638626.8559
9796.226621.4892 9825.83620.07129836.549620.75179849.465619.71829862.381  620.27
9872.969 618.527 9888.77617.86849904.571614.76889936.173616.96259967.775613.5925
9991.537608.341310017.51607.999710030.61608.225810043.55613.531210069.58632.7144
 10082.6644.0622 10093.1651.191910108.72653.989610148.08652.357310163.83654.0387
#Mann= 3 , 0 , 0
9499.944    0.12       09499.944    0.12       010163.83    0.12       0
#XS Ineff= 2 , 0
       0                               0
Bank Sta=9499.944,10163.83
Exp/Cntr=0.3,0.1

Type RM Length L Ch R = 1 ,4506.831,245.668100,245.668100,245.668100
XS GIS Cut Line= 6
479110.824592249798505.970040808479258.149582603798422.451878105
479468.910965128798325.249656848479647.752906825798232.460601152
479776.352367234798157.155787925  479853.9618671798105.727178249
#Sta/Elev= 30
9556.914681.84949643.563672.85889677.176666.36239689.082654.63129700.333 647.117
9755.947646.10929777.971 642.3179799.996626.47749833.033617.3745 9866.07613.9611
9888.094615.98469987.719605.306710021.49604.764210044.05607.422210077.89629.4609
10089.17628.310910123.01638.499210156.85639.605810168.28  650.2910179.77665.9917
10202.75690.779310214.24697.355510237.21696.510310248.84693.292710283.99676.5947
10307.42676.973710319.36680.551610331.33688.190710385.64733.097710402.11743.4192
#Mann= 3 , 0 , 0
9556.914    0.12       09556.914    0.12       010402.11    0.12       0
#XS Ineff= 2 , 0
       0                               0
Bank Sta=9556.914,10402.11
Exp/Cntr=0.3,0.1

Type RM Length L Ch R = 1 ,4261.163,79.587600,79.587600,79.587600
XS GIS Cut Line= 2
479138.851384025798667.705779633479918.861153781798434.715848386
#Sta/Elev= 30
9564.651668.16399633.688655.92119664.997641.68399713.864629.61269821.546627.5141
9842.419620.67349888.564611.97269936.348608.92739967.658600.9312 10009.4600.8766
10019.84601.576210040.71608.741510051.15615.279910061.59 625.61210072.02627.7113
 10092.9625.093110134.64627.080810145.08633.517510165.95639.843410197.26673.3618
10228.57695.132510249.45706.539310270.32708.318810280.76702.706510301.63 696.531
 10322.5697.360110353.81722.083610364.25 728.03510374.68728.492310378.71732.4809
#Mann= 3 , 0 , 0
9564.651    0.12       09564.651    0.12       010378.71    0.12       0
#XS Ineff= 2 , 0
       0                               0
Bank Sta=9564.651,10378.71
Exp/Cntr=0.3,0.1

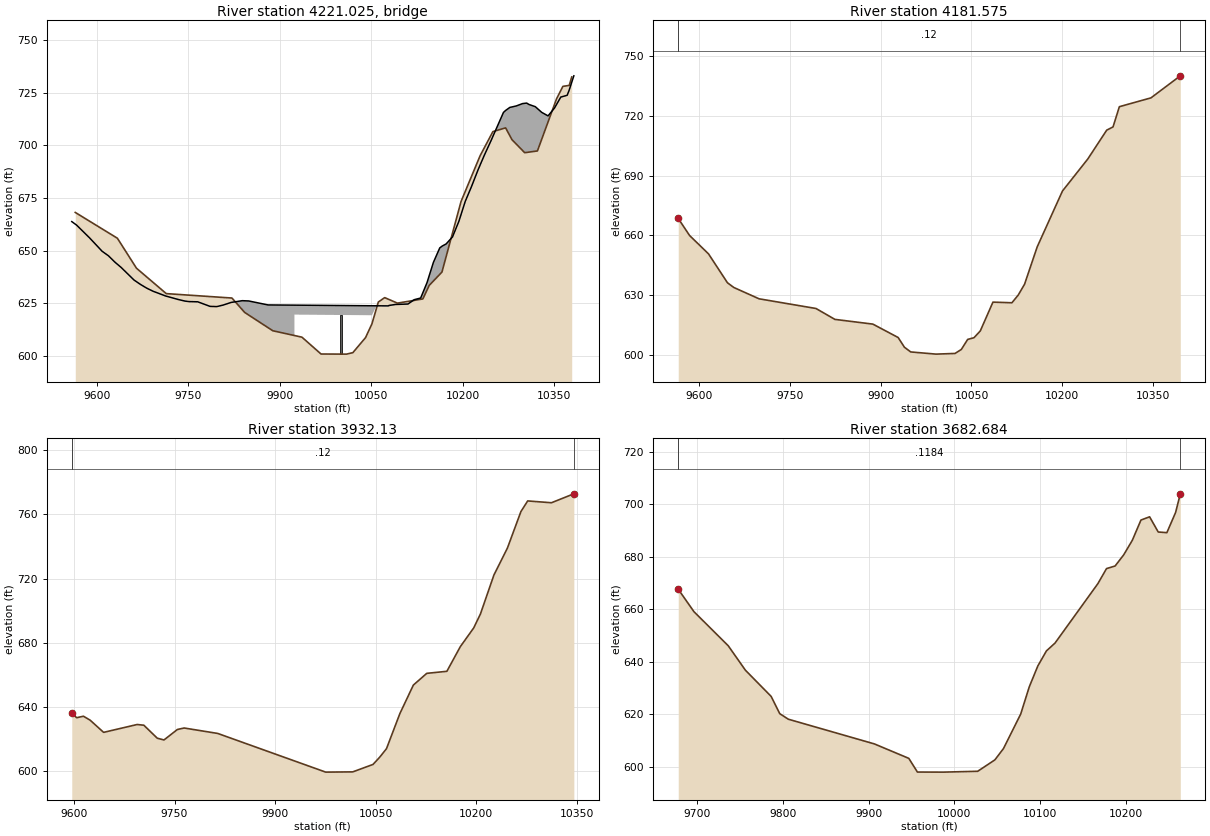
Type RM Length L Ch R = 3 ,4221.025,,,
BEGIN DESCRIPTION:
END DESCRIPTION:
Bridge Culvert--1,0,-1,-1, 0
Deck Dist Width WeirC Skew NumUp NumDn MinLoCord MaxHiCord MaxSubmerge Is_Ogee
26.834500,25.918600,2.6,0, 60, 60, , , 0.95, 0, 0,0,,
 9558.91 9566.96 9587.85 9608.74 9619.18 9629.63 9640.08 9660.97 9671.41 9681.86
 9692.30 9713.19 9734.08 9744.53 9751.06 9765.42 9785.68 9796.76 9807.20 9820.29
 9838.54 9848.98 9880.74 9924.05 9924.0510075.9510075.9510078.2310078.7810089.23
10110.1210120.5610131.0110141.4510151.9010162.3410166.4410172.7910183.2410193.68
10204.1310214.5710225.0210235.4610245.9110266.8010270.2810277.2410287.6910298.13
10304.9010308.5810319.0310329.4710339.9210350.3610360.8110371.2510374.1310382.21
  663.82  662.11  656.16  649.71  647.55  644.56  641.99  636.07  634.01  632.20
  630.73  628.45  626.78  626.07  625.82  625.73  623.55  623.45  624.18  625.43
  626.26  626.13  624.24  624.14  624.14  623.79  623.79  623.78  623.96  624.45
  624.67  626.74  627.52  634.84  644.45  651.33  652.22  653.21  656.55  663.94
  673.41  680.58  688.32  695.36  701.93  715.67  716.59  718.04  718.73  719.86
  720.10  719.45  718.39  715.70  714.02  717.70  722.95  723.80  725.88  733.04
 -336.18 -337.89 -343.84 -350.29 -352.45 -355.44 -358.01 -363.93 -365.99 -367.80
 -369.27 -371.55 -373.22 -373.93 -374.18 -374.27 -376.45 -376.55 -375.82 -374.57
 -373.74 -373.87 -375.76 -375.86  619.64  619.29 -376.21 -376.22 -376.04 -375.55
 -375.33 -373.26 -372.48 -365.16 -355.55 -348.67 -347.78 -346.79 -343.45 -336.06
 -326.59 -319.42 -311.68 -304.64 -298.07 -284.33 -283.41 -281.96 -281.27 -280.14
 -279.90 -280.55 -281.61 -284.30 -285.98 -282.30 -277.05 -276.20 -274.12 -266.96
 9558.91 9566.96 9587.85 9608.74 9619.18 9629.63 9640.08 9660.97 9671.41 9681.86
 9692.30 9713.19 9734.08 9744.53 9751.06 9765.42 9785.68 9796.76 9807.20 9820.29
 9838.54 9848.98 9880.74 9924.05 9924.0510075.9510075.9510078.2310078.7810089.23
10110.1210120.5610131.0110141.4510151.9010162.3410166.4410172.7910183.2410193.68
10204.1310214.5710225.0210235.4610245.9110266.8010270.2810277.2410287.6910298.13
10304.9010308.5810319.0310329.4710339.9210350.3610360.8110371.2510374.1310382.21
  663.82  662.11  656.16  649.71  647.55  644.56  641.99  636.07  634.01  632.20
  630.73  628.45  626.78  626.07  625.82  625.73  623.55  623.45  624.18  625.43
  626.26  626.13  624.24  624.14  624.14  623.79  623.79  623.78  623.96  624.45
  624.67  626.74  627.52  634.84  644.45  651.33  652.22  653.21  656.55  663.94
  673.41  680.58  688.32  695.36  701.93  715.67  716.59  718.04  718.73  719.86
  720.10  719.45  718.39  715.70  714.02  717.70  722.95  723.80  725.88  733.04
 -336.18 -337.89 -343.84 -350.29 -352.45 -355.44 -358.01 -363.93 -365.99 -367.80
 -369.27 -371.55 -373.22 -373.93 -374.18 -374.27 -376.45 -376.55 -375.82 -374.57
 -373.74 -373.87 -375.76 -375.86  619.64  619.29 -376.21 -376.22 -376.04 -375.55
 -375.33 -373.26 -372.48 -365.16 -355.55 -348.67 -347.78 -346.79 -343.45 -336.06
 -326.59 -319.42 -311.68 -304.64 -298.07 -284.33 -283.41 -281.96 -281.27 -280.14
 -279.90 -280.55 -281.61 -284.30 -285.98 -282.30 -277.05 -276.20 -274.12 -266.96
Pier Skew, UpSta & Num, DnSta & Num=  ,10000.00, 2 ,10000.00, 2 , 0 , 0 , 0 ,,
    4.00    4.00
 -376.04  623.96
    4.00    4.00
 -376.04  623.96
BR Coef=-1 , 0 , 0 ,, 0 ,,,0.8,0,1,0,
WSPro=,,,, 1 ,,,, 0 ,,,, 0 ,,,,-1 ,-1 ,-1 , 0 , 0 , 0 , 0 , 0
BC Design=,, 0 ,, 0 ,,,,,,

Type RM Length L Ch R = 1 ,4181.575,249.445700,249.445700,249.445700
XS GIS Cut Line= 2
479147.083893599798746.641018477479941.430598226798509.368626164
#Sta/Elev= 30
9565.816668.51069584.515659.97969615.824 650.7769647.134636.30219657.571633.9519
9699.317628.27659793.246623.43519824.556617.97739887.176615.61889928.922608.9129
9939.358604.01989949.795601.68449991.541600.591210022.85600.931710033.29602.9348
10043.72607.947410054.16608.8106 10064.6612.221310085.47626.618310116.78626.2983
10127.22630.163610137.65635.568210158.53654.266810200.27682.238210242.02698.2365
10273.33712.701610283.77714.3193 10294.2724.441210346.39728.863510394.84739.8941
#Mann= 3 , 0 , 0
9565.816    0.12       09565.816    0.12       010394.84    0.12       0
#XS Ineff= 2 , 0
       0                               0
Bank Sta=9565.816,10394.84
Exp/Cntr=0.3,0.1

Type RM Length L Ch R = 1 , 3932.13,249.445700,249.445700,249.445700
XS GIS Cut Line= 6
479157.668113179 798848.12500631479311.879093305798844.383672843
479619.151744784 798877.72099391479713.282779259798881.864485826
479830.957789498798872.481416349479902.300718919798857.395583028
#Sta/Elev= 30
9596.756636.0229 9604.12633.36719614.164634.27959624.207631.80269644.261624.2253
9694.273629.12269704.276628.67329724.282620.59639734.286619.49759754.301626.0168
9764.333626.94379814.492623.55399975.559599.450410015.88599.600810046.08604.2409
10056.15608.784610066.19614.043410086.24635.985710106.29653.696610126.29660.9993
 10156.3662.278810176.32677.624810196.33689.320210206.34698.007410226.47722.2947
10246.59739.059610266.71761.798610276.82768.441310312.22 767.30510345.67772.8635
#Mann= 3 , 0 , 0
9596.756    0.12       09596.756    0.12       010345.67    0.12       0
#XS Ineff= 2 , 0
       09768.131                       0
Bank Sta=9596.756,10345.67
Exp/Cntr=0.3,0.1

Type RM Length L Ch R = 1 ,3682.684,0.000000,0.000000,0.000000
XS GIS Cut Line= 6
 479206.68329682799101.722961879479303.585411257799100.759817213
479593.871415237799123.379232521479682.445965098799125.569297266
479733.291564918799122.609178178479790.374308009799114.430909675
#Sta/Elev= 30
9678.153667.62099696.471659.07249736.473646.07799756.474 636.7719786.491626.7932
9796.505620.22379806.519618.10799906.792608.70389946.962603.19769957.004597.9829
9987.132597.954410027.27 598.27810047.34602.628710057.37606.9549 10077.4620.0606
 10087.4630.4396 10097.4638.402810107.41644.132810117.41647.106110167.44669.7723
10177.46675.476410187.48676.471110197.49 680.71310207.52686.2452 10217.6693.9691
10227.68695.206910237.76689.408610247.83689.172810258.01696.859410263.49703.9578
#Mann= 3 , 0 , 0
9678.153  0.1184       09678.153  0.1184       010263.49  0.1184       0
#XS Ineff= 2 , 0
       0                               0
Bank Sta=9678.153,10263.49
Exp/Cntr=0.3,0.1